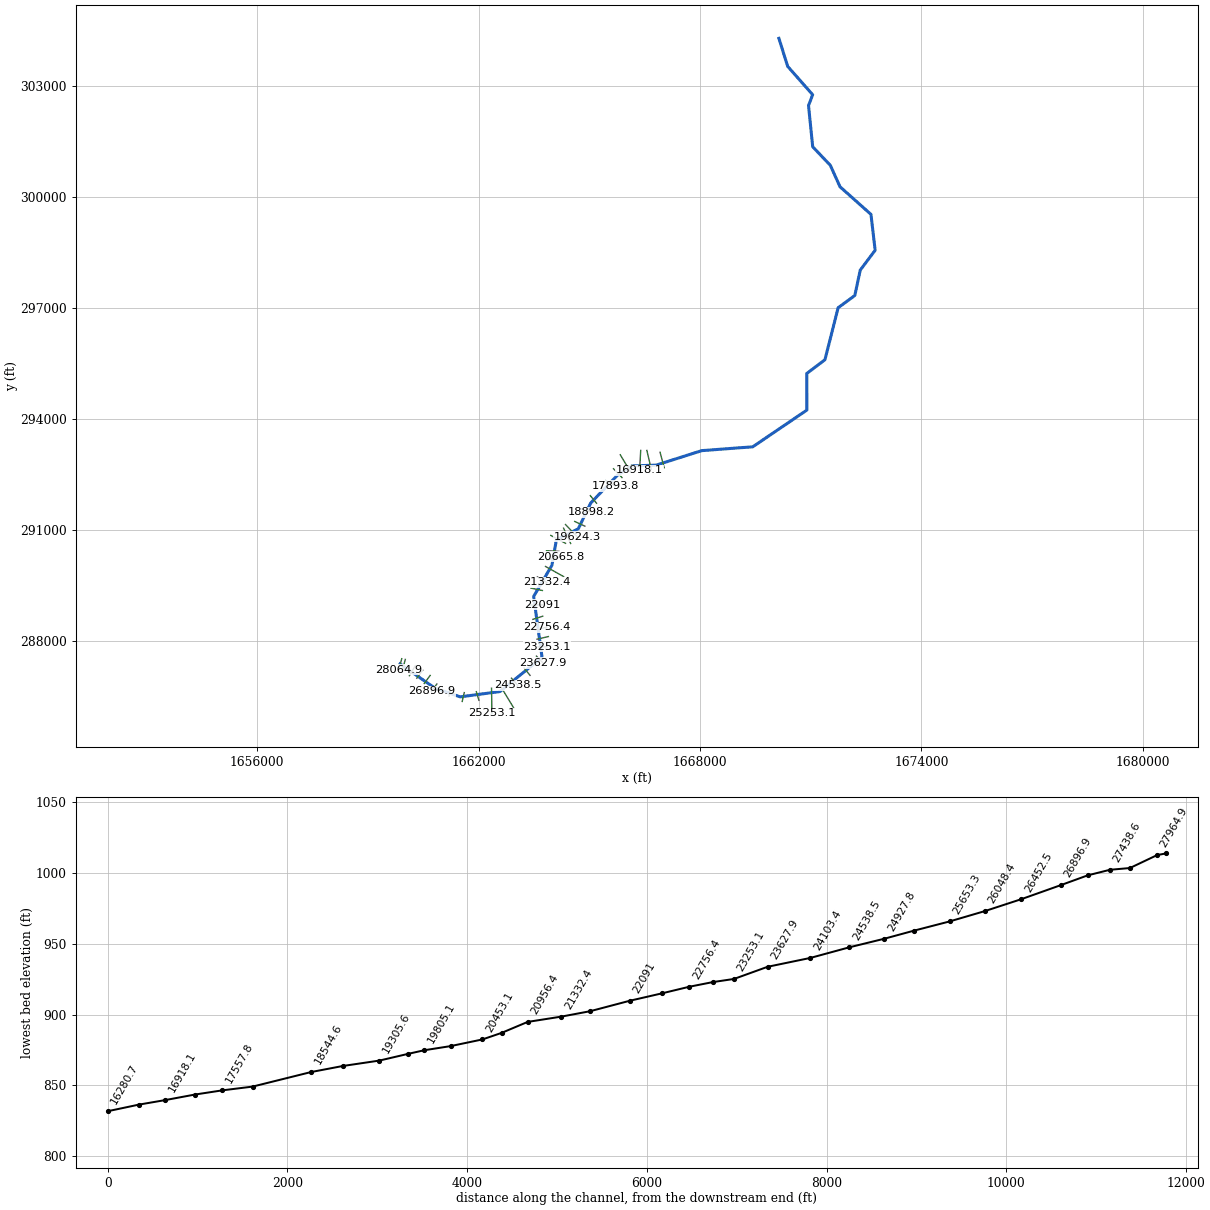
--- WHITMANCRK.prj (project) ---

Proj Title=WHITMANCRK
Current Plan=p01
Default Exp/Contr=0,0
English Units
Geom File=g01
Flow File=f01
Plan File=p01
BEGIN DESCRIPTION:
END DESCRIPTION:
DSS Export Rating Curves= 0
DSS Export Rating Curve Sorted= 0
DSS Export Volume Flow Curves= 0
DXF OffsetX= 0
DXF OffsetY= 0
DXF ScaleX= 0
DXF ScaleY= 0

--- WHITMANCRK.p01 (plan) ---

Plan Title=Floodplain
Program Version=4.00
Geom File=g01
Flow File=f01
K Sum by GR=0
Std Step Tol=0.01
Critical Tol=0.01
Num of Std Step Trials=20
Max Error Tol=0.3
Flow Tol Ratio=0.001
Split Flow NTrial=30
Split Flow Tol=0.02
Split Flow Ratio=0.02
Log Output Level=0
Friction Slope Method=1
Unsteady Friction Slope Method=2
Unsteady Bridges Friction Slope Method=1
Global Log Level=0
CheckData=False
Run HTab=0
Run UNet=0
Run PostProcess=0
UNET Theta=0
UNET Theta Warmup=0
UNET ZTol=0
UNET ZSATol=0
UNET MxIter=0
UNET MaxInSteps=0
UNET DtIC=0
UNET DtMin=0
UNET MaxCRTS=0
UNET WFStab=0
UNET SFStab=0
UNET WFX=0
UNET SFX=0
UNET DSS MLevel=0
UNET DZMax Abort=0
UNET Convert EG Bridges=0
UNET Use Existing IB Tables=0
UNET Froude Limit=0
UNET Froude Power=0
Write IC File=0
Echo Input=False
Echo Output=False
Write Detailed=0

--- WHITMANCRK.f01 (steady flow) ---

Flow Title=NFF Regression Equation
Program Version=4.00
Number of Profiles=1
Profile Names=P100yr
River Rch & RM=WHITMANCRK,Main      ,28064.9
897.6510
River Rch & RM=WHITMANCRK,Main      ,24927.8
987.8857
River Rch & RM=WHITMANCRK,Main      ,24538.5
1335.492
River Rch & RM=WHITMANCRK,Main      ,22091
1429.815
River Rch & RM=WHITMANCRK,Main      ,20098.3
1585.229
River Rch & RM=WHITMANCRK,Main      ,17251.2
1650.235
River Rch & RM=WHITMANCRK,Main      ,16629.3
1827.746
River Rch & RM=WHITMANCRK,Main      ,12915.9
1938.141
River Rch & RM=WHITMANCRK,Main      ,12630.4
2745.134
River Rch & RM=WHITMANCRK,Main      ,10451.2
2771.110
River Rch & RM=WHITMANCRK,Main      ,51.5
3072.592
Boundary for River Rch & Prof#=WHITMANCRK,Main      ,1
Up Type=0
Dn Type=3
Dn Slope=0.01367

--- WHITMANCRK.g01 (geometry) ---

Geom Title=USGS 10m DEM
Program Version=4.10

River Reach=WHITMANCRK      ,Main
Reach XY= 30
     1659870.604      287389.092     1660811.896       286735.23
     1661499.357      286497.522     1662578.482      286640.893
     1663719.313      287568.613     1663491.147      289212.104
     1663988.016      290056.434     1664107.311       290742.09
     1664702.627      291043.223     1665037.958      291737.894
     1665753.782       292480.73     1666152.697      292741.149
     1666809.399      292761.996     1668048.676      293154.627
     1669429.254      293257.707     1670895.539      294250.287
     1670893.223      295240.551     1671385.459      295611.176
     1671743.344      297017.235     1672195.043      297348.481
     1672342.135      298034.137     1672746.348      298571.543
     1672632.844      299542.117     1671794.305         300288.
     1671532.551      300867.102     1671054.213      301369.762
     1670940.709      302482.795     1671053.055      302776.979
     1670375.506      303543.709     1670138.074      304301.174

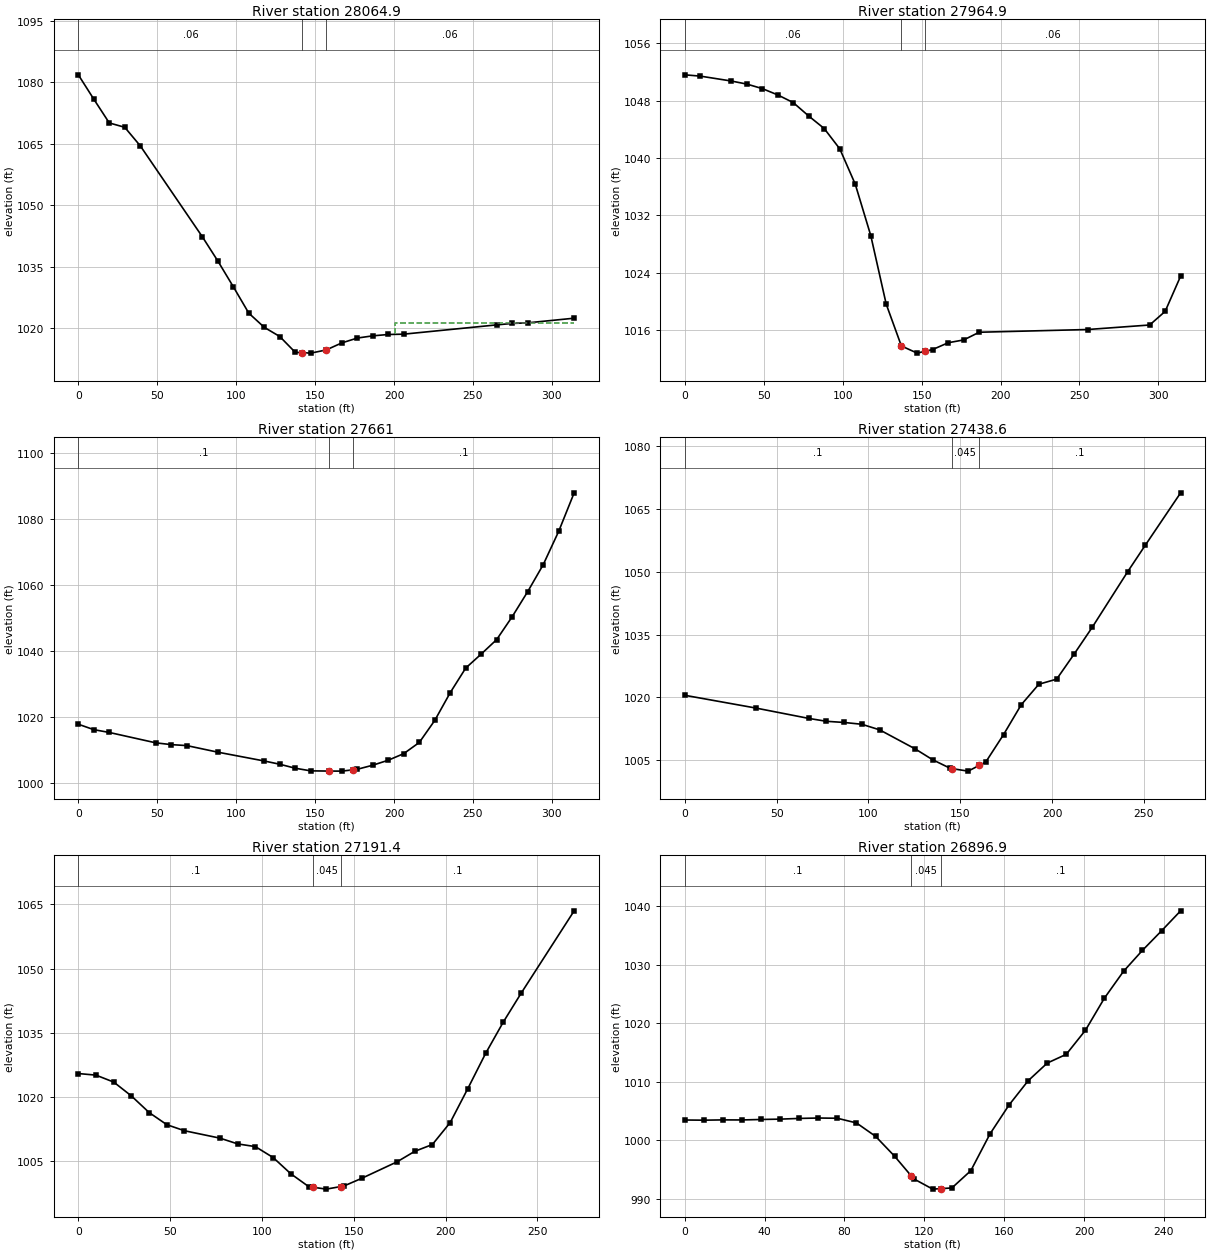
Type RM Length L Ch R = 1 ,28064.9 ,100,99.9,99.8
XS GIS Cut Line= 2
     1659917.324      287529.522     1659833.595      287226.778
#Sta/Elev= 24
       0 1081.77     9.8 1075.84    19.6 1070.05    29.4 1068.99    39.3 1064.44
    78.5 1042.35    88.3 1036.46    98.2 1030.13     108  1023.7   117.8 1020.25
   127.6 1018.02   137.4 1014.17     142 1014.08   147.2 1013.97     157 1014.74
   166.9 1016.46   176.7 1017.64   186.5 1018.18   196.3 1018.51   206.1 1018.59
     265 1020.85   274.8  1021.2   284.7 1021.35   314.1 1022.48
#Mann= 3 , 0 , 0
       0     .06       0     142    .045       0     157     .06       0
#XS Ineff= 2 , 0
                          200.46         1021.43
Permanent Ineff=
       F       F
Bank Sta=142,157
XS Rating Curve= 0 ,0
Exp/Cntr=0.3,0.1

Type RM Length L Ch R = 1 ,27964.9 ,309.4,303.7,297.9
XS GIS Cut Line= 2
     1660013.725      287510.047     1659929.996      287207.304
#Sta/Elev= 24
       0 1051.58     9.8  1051.4    29.4 1050.72    39.3 1050.29    49.1 1049.66
    58.9 1048.78    68.7 1047.71    78.5 1045.84    88.3  1044.1    98.2 1041.26
     108 1036.33   117.8 1029.19   127.6 1019.62   137.2  1013.8   147.2  1012.8
   152.2 1013.06     157  1013.3   166.9 1014.25   176.7 1014.64   186.5 1015.71
   255.2 1016.09   294.5 1016.72   304.3 1018.62   314.1 1023.53
#Mann= 3 , 0 , 0
       0     .06       0   137.2    .045       0   152.2     .06       0
Bank Sta=137.2,152.2
XS Rating Curve= 0 ,0
Exp/Cntr=0.3,0.1

Type RM Length L Ch R = 1 ,27661   ,224.4,222.1,219.7
XS GIS Cut Line= 2
     1660283.862      287339.371     1660123.919      287069.033
#Sta/Elev= 29
       0 1017.83     9.8 1016.19    19.6 1015.34    49.1 1012.19    58.9 1011.65
    68.7 1011.36    88.3 1009.37   117.8 1006.69   127.6 1005.71   137.4  1004.5
   147.2  1003.7   158.8 1003.64   166.9 1003.62   173.8 1004.01   176.7 1004.18
   186.5 1005.41   196.3 1006.92   206.1 1008.91     216 1012.31   225.8 1018.99
   235.6 1027.41   245.4 1034.85   255.2 1039.09     265 1043.48   274.8 1050.39
   284.7 1058.04   294.5 1066.19   304.3 1076.29   314.1 1087.96
#Mann= 3 , 0 , 0
       0      .1       0   158.8    .045       0   173.8      .1       0
Bank Sta=158.8,173.8
XS Rating Curve= 0 ,0
Exp/Cntr=0.3,0.1

Type RM Length L Ch R = 1 ,27438.6 ,247.2,247.2,247.2
XS GIS Cut Line= 2
     1660486.525      287219.168     1660326.048      287002.052
#Sta/Elev= 23
       0 1020.49    38.6 1017.45    67.5 1014.97    77.1 1014.28    86.8    1014
    96.4 1013.57   106.1 1012.24   125.4  1007.7     135 1005.09   144.6 1003.04
   145.3 1002.99   154.3 1002.38   160.3 1003.74   163.9 1004.56   173.6 1011.12
   183.2 1018.23   192.8 1023.13   202.5 1024.35   212.1 1030.39   221.8 1036.68
   241.1 1049.96   250.7 1056.29     270 1068.84
#Mann= 3 , 0 , 0
       0      .1       0   145.3    .045       0   160.3      .1       0
Bank Sta=145.3,160.3
XS Rating Curve= 0 ,0
Exp/Cntr=0.3,0.1

Type RM Length L Ch R = 1 ,27191.4 ,294.4,294.4,294.4
XS GIS Cut Line= 2
      1660686.87      287076.479     1660526.393      286859.362
#Sta/Elev= 27
       0 1025.47     9.6  1025.1    19.3 1023.47    28.9 1020.23    38.6 1016.34
    48.2 1013.51    57.8  1012.1    77.1 1010.37    86.8 1009.02    96.4 1008.39
   106.1 1005.83   115.7 1002.04   125.4  999.05   127.9  998.89     135  998.45
   142.9  999.05   144.6  999.18   154.3 1000.97   173.6 1004.84   183.2 1007.29
   192.8 1008.88   202.5 1014.02   212.1 1021.96   221.8 1030.19   231.4  1037.5
   241.1 1044.23     270 1063.51
#Mann= 3 , 0 , 0
       0      .1       0   127.9    .045       0   142.9      .1       0
Bank Sta=127.9,142.9
XS Rating Curve= 0 ,0
Exp/Cntr=0.3,0.1

Type RM Length L Ch R = 1 ,26896.9 ,434.4,444.3,454.2
XS GIS Cut Line= 2
     1660868.652      286845.392      1660721.15      286645.467
#Sta/Elev= 29
       0 1003.46     9.6 1003.43    19.1 1003.48    28.7 1003.47    38.2 1003.55
    47.8 1003.61    57.3 1003.73    66.9  1003.8    76.4 1003.76      86 1002.96
    95.6 1000.66   105.1  997.27   113.4  993.92   114.7   993.4   124.2  991.64
   128.4  991.73   133.8  991.84   143.3   994.8   152.9 1001.08   162.4 1006.01
     172 1010.17   181.6  1013.2   191.1 1014.69   200.7  1018.8   210.2 1024.29
   219.8 1028.89   229.3 1032.48   238.9 1035.83   248.4 1039.23
#Mann= 3 , 0 , 0
       0      .1       0   113.4    .045       0   128.4      .1       0
Bank Sta=113.4,128.4
XS Rating Curve= 0 ,0
Exp/Cntr=0.3,0.1

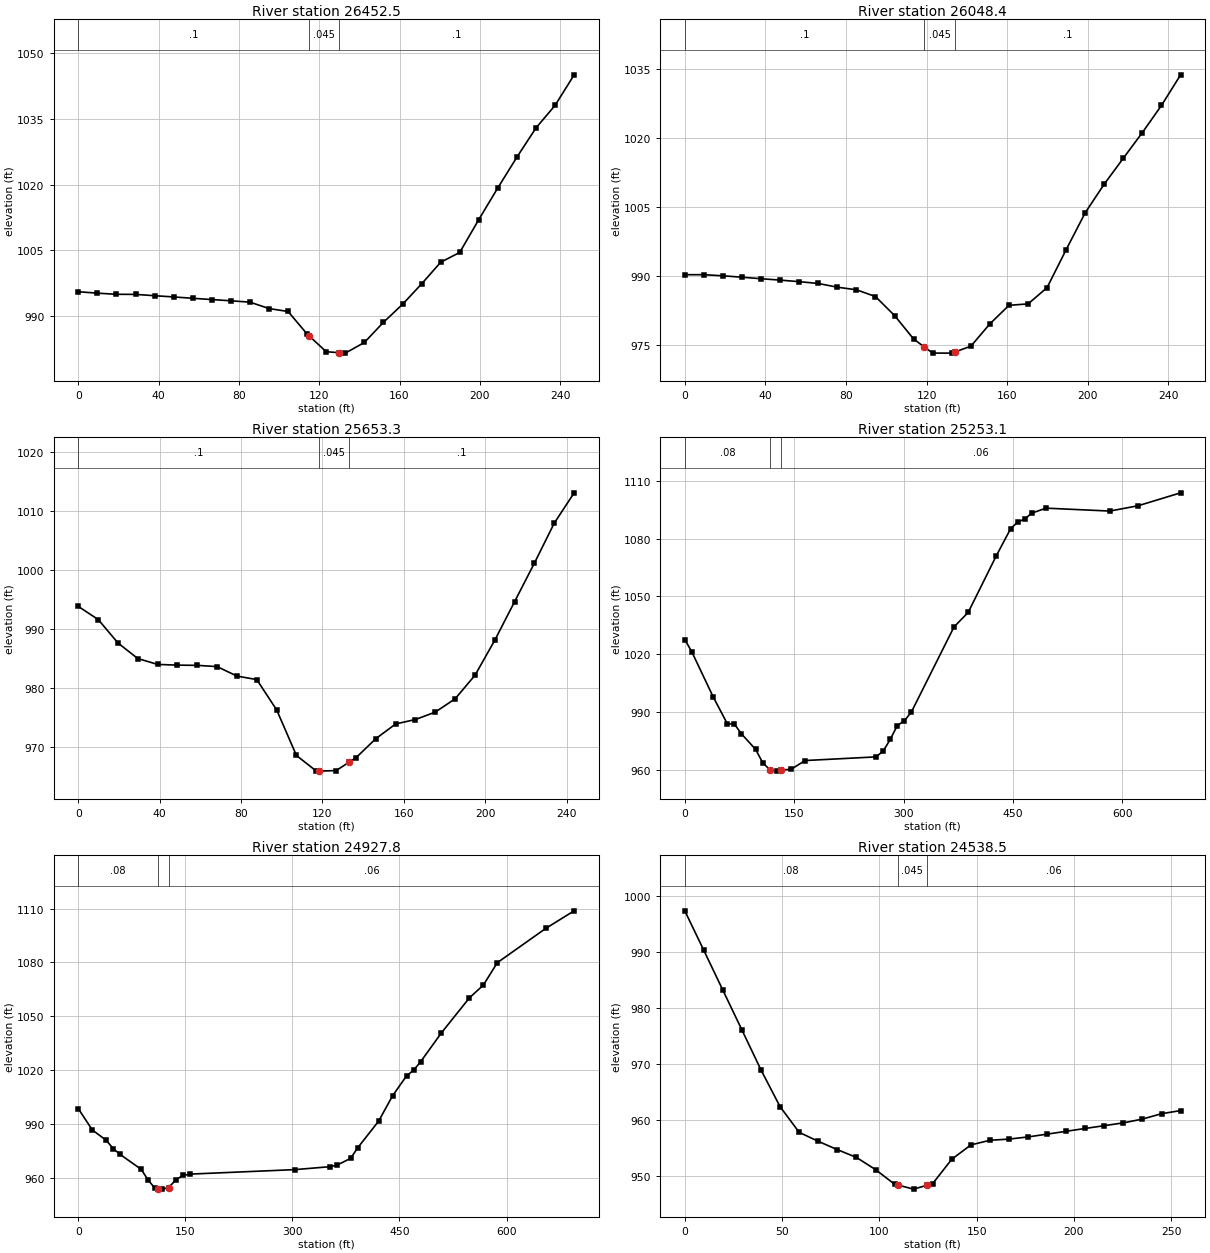
Type RM Length L Ch R = 1 ,26452.5 ,404.8,404,403.1
XS GIS Cut Line= 2
     1661245.928      286758.321     1661197.394      286516.145
#Sta/Elev= 29
       0  995.59     9.5  995.27      19  995.01    28.5  994.99      38  994.69
    47.5  994.41      57   994.1    66.5  993.81      76  993.53    85.5  993.22
      95  991.76   104.5  991.09     114  985.93     115  985.51   123.5  981.92
     130   981.7     133   981.6   142.5  984.03     152  988.63   161.5  992.72
     171  997.38   180.5 1002.31     190 1004.56   199.5 1012.05     209 1019.29
   218.5 1026.29     228 1032.94   237.5 1038.08     247 1045.04
#Mann= 3 , 0 , 0
       0      .1       0     115    .045       0     130      .1       0
Bank Sta=115,130
XS Rating Curve= 0 ,0
Exp/Cntr=0.3,0.1

Type RM Length L Ch R = 1 ,26048.4 ,382.9,394.7,406.5
XS GIS Cut Line= 2
     1661611.674      286612.732     1661555.121       286373.25
#Sta/Elev= 29
       0  990.28     9.5  990.28    18.9  990.04    28.4  989.73    37.9   989.4
    47.3   989.1    56.8  988.76    66.2  988.37    75.7  987.56    85.2  986.99
    94.6  985.53   104.1  981.39   113.6  976.26   118.9  974.54     123  973.21
   132.5   973.2   133.9  973.42     142  974.71   151.4  979.56   160.9  983.61
   170.4  983.92   179.8  987.46   189.3  995.74   198.8 1003.81   208.2 1010.01
   217.7 1015.67   227.1 1021.22   236.6 1027.14   246.1  1033.8
#Mann= 3 , 0 , 0
       0      .1       0   118.9    .045       0   133.9      .1       0
Bank Sta=118.9,133.9
XS Rating Curve= 0 ,0
Exp/Cntr=0.3,0.1

Type RM Length L Ch R = 1 ,25653.3 ,406.2,400.1,393.9
XS GIS Cut Line= 2
     1661938.566       286637.89     1662008.109       286404.34
#Sta/Elev= 28
       0  993.76     9.8  991.53    19.5  987.56    29.2  984.93      39  983.93
    48.7  983.81    58.5  983.77    68.2  983.56      78  981.95    87.7  981.36
    97.5  976.21   107.2  968.49     117  965.84   118.2  965.85   126.7  965.93
   133.2  967.38   136.5  968.12   146.2  971.34     156  973.84   165.7  974.59
   175.4  975.84   185.2   978.1     195  982.11   204.7  988.04   214.4  994.55
   224.2 1001.13   233.9 1007.87   243.7 1013.02
#Mann= 3 , 0 , 0
       0      .1       0   118.2    .045       0   133.2      .1       0
Bank Sta=118.2,133.2
XS Rating Curve= 0 ,0
Exp/Cntr=0.3,0.1

Type RM Length L Ch R = 1 ,25253.1 ,313.3,325.3,337.2
XS GIS Cut Line= 2
     1662350.257      286730.877     1662362.122      286050.976
#Sta/Elev= 30
       0 1027.58     9.7 1021.15    38.9  997.85    58.3  983.85      68  983.73
    77.7   978.6    97.1  970.56   106.9  963.61   117.5  959.66   126.3  959.26
   132.5   959.8   145.7  960.22   165.1  964.76   262.3  966.66     272  969.64
   281.7  975.69   291.4  982.89   301.1  985.38   310.9  990.07   369.2 1034.15
   388.6 1041.66   427.4 1071.23   446.9 1085.18   456.6 1088.59   466.3 1090.25
     476 1093.26   495.4 1095.83   582.9 1094.32   621.7 1097.08     680 1103.79
#Mann= 3 , 0 , 0
       0     .08       0   117.5    .045       0   132.5     .06       0
Bank Sta=117.5,132.5
XS Rating Curve= 0 ,0
Exp/Cntr=0.3,0.1

Type RM Length L Ch R = 1 ,24927.8 ,385.1,389.2,393.4
XS GIS Cut Line= 2
     1662591.503      286791.073     1662952.079      286197.181
#Sta/Elev= 30
       0  998.44    19.6   986.6    39.1  980.83    48.9   976.2    58.7  972.93
    88.1  964.66    97.9  958.63   107.6  954.02   111.4  953.87   117.4  953.63
   126.4  954.43     137  958.98   146.8  961.26   156.6     962   303.4   964.5
   352.3  966.12   362.1  966.92   381.6  970.79   391.4  976.62   420.8  991.52
   440.4 1005.68   459.9 1016.73   469.7 1019.85   479.5 1024.53   508.8 1040.72
     548 1060.21   567.6 1067.35   587.1 1079.82   655.6 1099.08   694.8 1108.72
#Mann= 3 , 0 , 0
       0     .08       0   111.4    .045       0   126.4     .06       0
Bank Sta=111.4,126.4
XS Rating Curve= 0 ,0
Exp/Cntr=0.3,0.1

Type RM Length L Ch R = 1 ,24538.5 ,436,434.9,433.8
XS GIS Cut Line= 2
     1662890.425      287002.613     1663060.044      286812.547
#Sta/Elev= 29
       0  997.41     9.8  990.31    19.6  983.17    29.4  976.04    39.2  968.88
      49  962.31    58.8  957.73    68.6  956.12    78.4  954.63    88.2  953.24
      98  951.06   107.8  948.44   109.4   948.3   117.6  947.56   124.4  948.25
   127.4  948.56   137.2  952.91     147  955.48   156.8  956.31   166.6  956.52
   176.4  956.91   186.2  957.41     196  957.92   205.8  958.43   215.6  958.93
   225.4  959.43   235.2  960.11     245  961.07   254.8  961.63
#Mann= 3 , 0 , 0
       0     .08       0   109.4    .045       0   124.4     .06       0
Bank Sta=109.4,124.4
XS Rating Curve= 0 ,0
Exp/Cntr=0.3,0.1

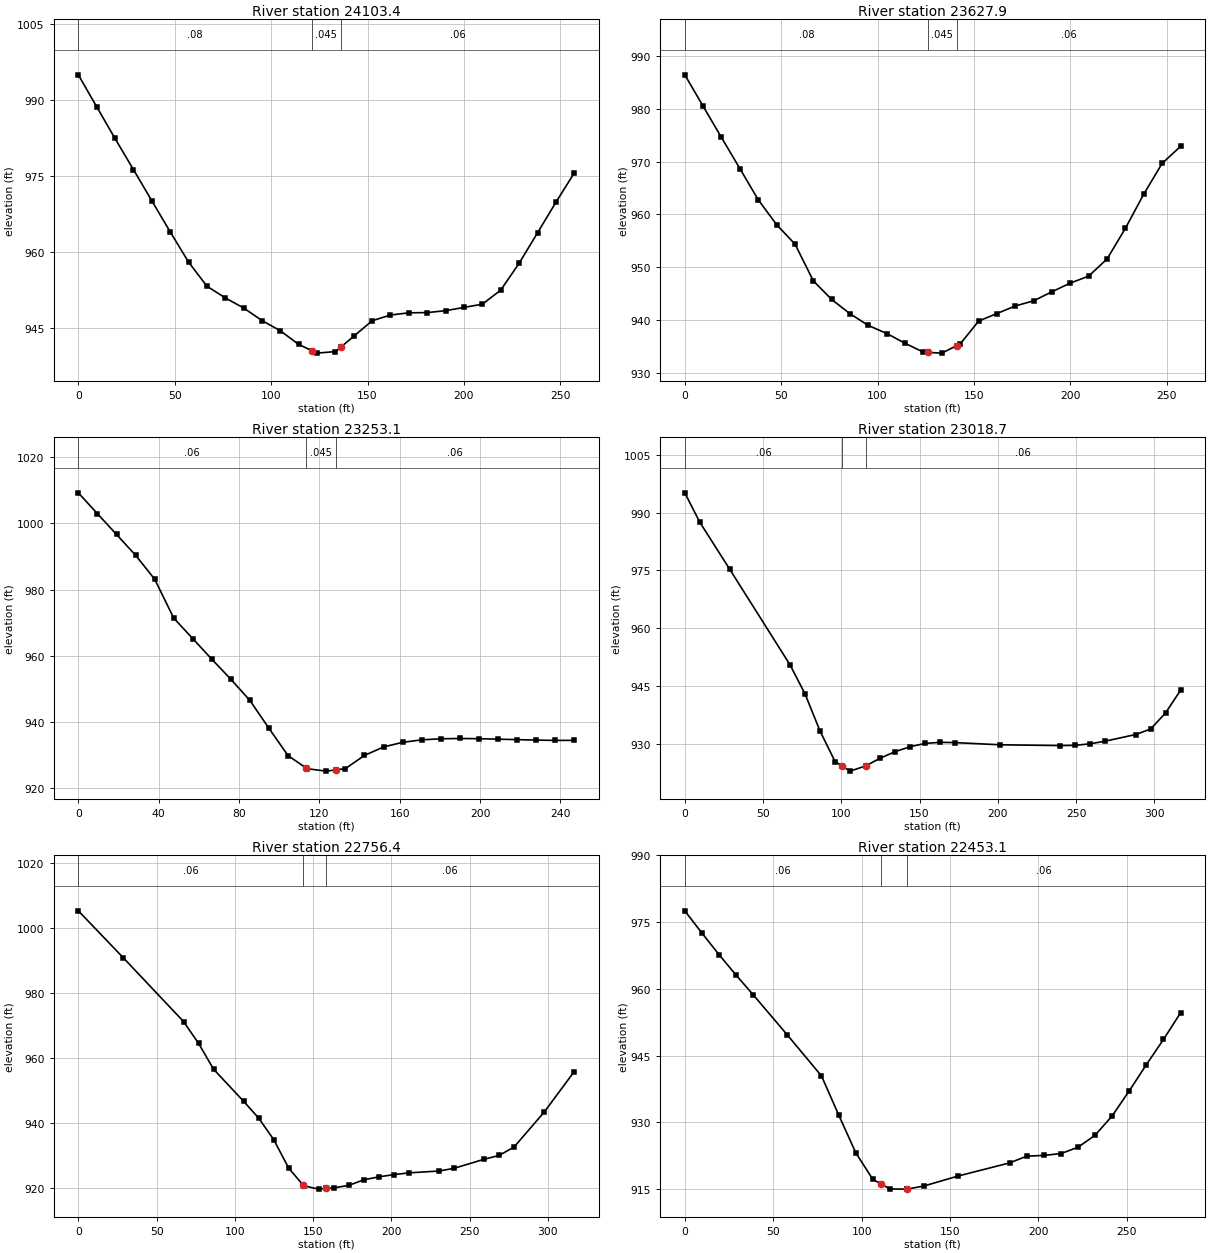
Type RM Length L Ch R = 1 ,24103.4 ,473.6,475.4,477.3
XS GIS Cut Line= 2
     1663232.381      287278.668     1663393.888      287078.502
#Sta/Elev= 30
       0   994.9     9.5  988.61      19  982.37    28.6  976.21    38.1  970.08
    47.6  963.98    57.2  957.97    66.7  953.23    76.2  950.93    85.7  948.94
    95.3  946.45   104.8  944.44   114.3  941.74   121.1  940.52   123.8  940.03
   133.4  940.34   136.1   941.2   142.9  943.36   152.4  946.41   161.9  947.54
   171.5  947.98     181  948.02   190.5   948.4     200  949.04   209.6  949.68
   219.1  952.45   228.6  957.72   238.2  963.75   247.7  969.75   257.2  975.52
#Mann= 3 , 0 , 0
       0     .08       0   121.1    .045       0   136.1     .06       0
Bank Sta=121.1,136.1
XS Rating Curve= 0 ,0
Exp/Cntr=0.3,0.1

Type RM Length L Ch R = 1 ,23627.9 ,355.7,374.5,393.3
XS GIS Cut Line= 2
     1663567.352      287599.642     1663744.938      287413.653
#Sta/Elev= 30
       0  986.39     9.5  980.46      19  974.55    28.6  968.65    38.1  962.76
    47.6  958.07    57.2  954.36    66.7  947.42    76.2  943.91    85.7  941.22
    95.2     939   104.8  937.48   114.3  935.62   123.8  933.95   126.1  933.91
   133.3  933.77   141.1  935.19   142.9  935.52   152.4  939.82   161.9  941.26
   171.4  942.68     181  943.67   190.5  945.38     200  947.02   209.5  948.33
   219.1   951.6   228.6   957.4   238.1  963.85   247.6  969.64   257.2  972.88
#Mann= 3 , 0 , 0
       0     .08       0   126.1    .045       0   141.1     .06       0
Bank Sta=126.1,141.1
XS Rating Curve= 0 ,0
Exp/Cntr=0.3,0.1

Type RM Length L Ch R = 1 ,23253.1 ,229.7,234.4,239.1
XS GIS Cut Line= 2
     1663607.719      287848.216     1663854.486      287852.775
#Sta/Elev= 29
       0 1009.23     9.5 1002.94      19  996.65    28.5  990.37      38  983.13
    47.5  971.37      57  965.17    66.4  958.99    75.9  952.92    85.4  946.51
    94.9  938.07   104.4  929.84   113.3  926.14   113.9  925.89   123.4  925.16
   128.3  925.55   132.9  925.91   142.4  929.89   151.9  932.46   161.4  933.85
   170.9  934.61   180.4  934.93   189.8  935.02   199.4  934.96   208.8  934.82
   218.3  934.67   227.8  934.54   237.3  934.44   246.8  934.45
#Mann= 3 , 0 , 0
       0     .06       0   113.3    .045       0   128.3     .06       0
Bank Sta=113.3,128.3
XS Rating Curve= 0 ,0
Exp/Cntr=0.3,0.1

Type RM Length L Ch R = 1 ,23018.7 ,262,262.1,262.1
XS GIS Cut Line= 2
      1663582.62       288056.46      1663891.25      288127.859
#Sta/Elev= 25
       0  995.15     9.6  987.51    28.8  975.26    67.2  950.54    76.8  943.01
    86.4  933.35      96  925.44   100.5  924.27   105.6  922.95   115.5  924.29
   124.8  926.29   134.4  928.01     144  929.29   153.6  930.14   163.2  930.42
   172.8  930.35   201.6  929.78     240  929.58   249.6  929.65   259.2  930.05
   268.8  930.74     288  932.44   297.6  933.86   307.2  938.06   316.8  943.94
#Mann= 3 , 0 , 0
       0     .06       0   100.5    .045       0   115.5     .06       0
Bank Sta=100.5,115.5
XS Rating Curve= 0 ,0
Exp/Cntr=0.3,0.1

Type RM Length L Ch R = 1 ,22756.4 ,301.6,303.4,305.2
XS GIS Cut Line= 2
     1663533.738      288308.661     1663842.368       288380.06
#Sta/Elev= 26
       0 1005.34    28.8  990.85    67.2  971.26    76.8  964.56    86.4  956.58
   105.6   946.7   115.2  941.55   124.8  934.93   134.4  926.13   143.4  921.03
     144  920.69   153.6  919.66   158.4  919.86   163.2  920.05   172.8  920.82
   182.4  922.53     192  923.43   201.6  924.13   211.2  924.66   230.4  925.24
     240  926.05   259.2  928.85   268.8  930.03   278.4  932.62   297.6  943.34
   316.8  955.83
#Mann= 3 , 0 , 0
       0     .06       0   143.4    .045       0   158.4     .06       0
Bank Sta=143.4,158.4
XS Rating Curve= 0 ,0
Exp/Cntr=0.3,0.1

Type RM Length L Ch R = 1 ,22453.1 ,368.6,362,355.5
XS GIS Cut Line= 2
     1663470.354       288592.89     1663737.436      288678.129
#Sta/Elev= 27
       0  977.56     9.7  972.56    19.3  967.74      29  963.11    38.7  958.68
      58  949.65    77.3  940.45      87   931.7    96.7  923.17   106.3  917.21
   110.8   916.2     116  915.03   125.7     915   125.8  915.01   135.3  915.71
   154.7  917.96   183.7   920.9   193.4  922.41     203  922.58   212.7  922.99
   222.4  924.42     232  927.11   241.7  931.46   251.4  937.12     261  942.97
   270.7  948.64   280.4  954.65
#Mann= 3 , 0 , 0
       0     .06       0   110.8    .045       0   125.8     .06       0
Bank Sta=110.8,125.8
XS Rating Curve= 0 ,0
Exp/Cntr=0.3,0.1

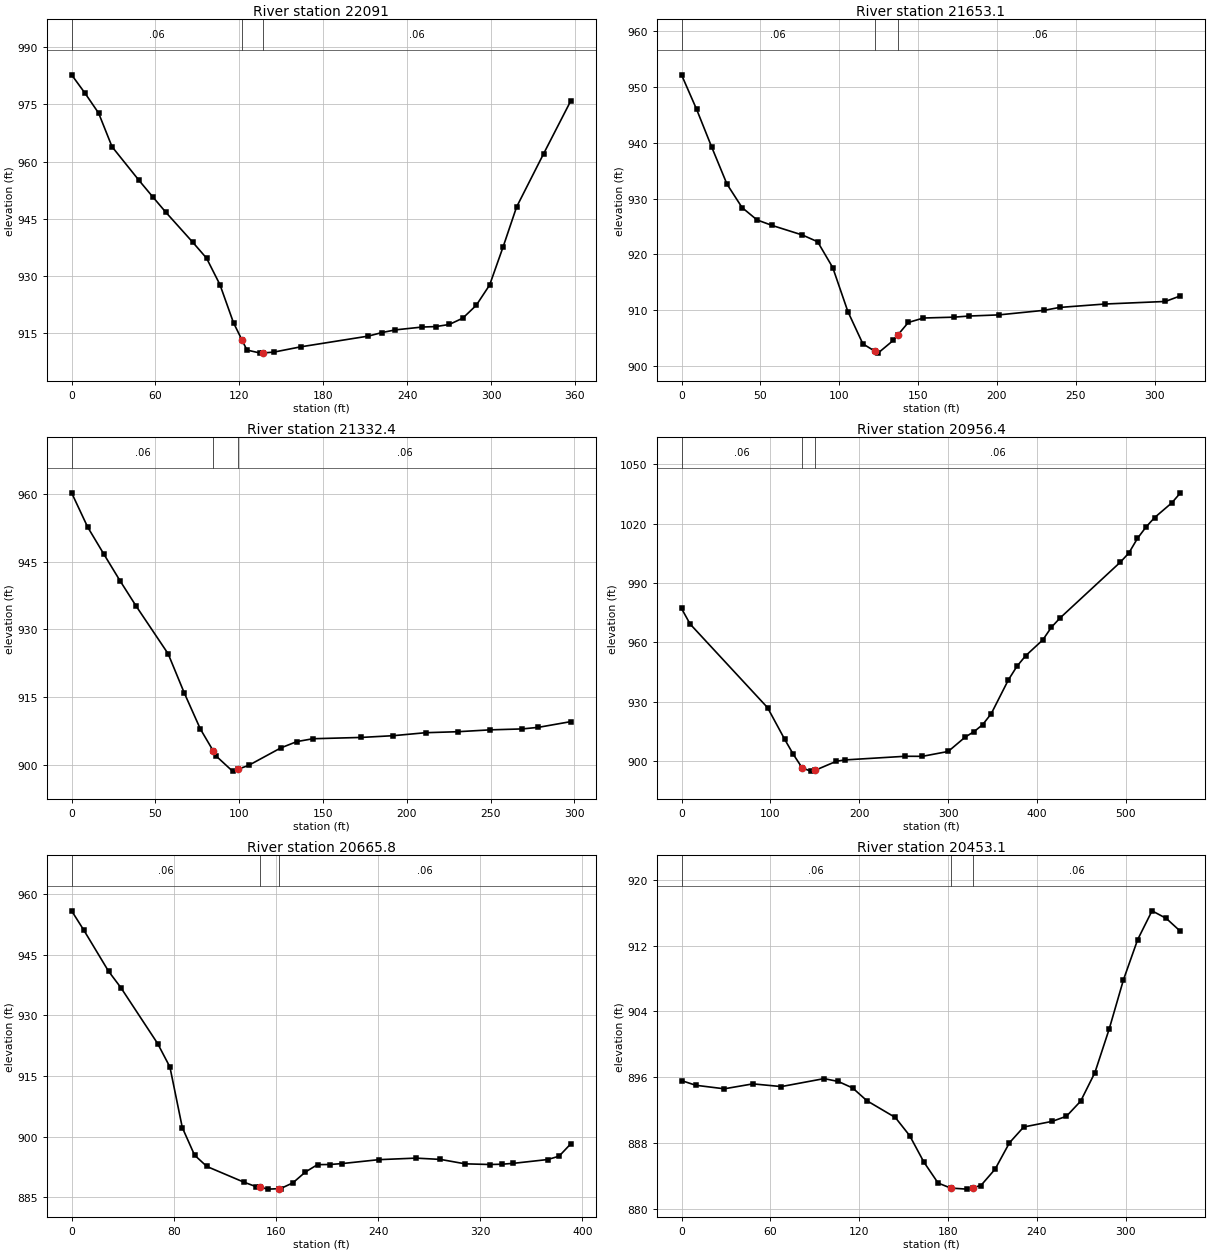
Type RM Length L Ch R = 1 ,22091   ,442.7,437.7,432.7
XS GIS Cut Line= 2
     1663379.857      288979.409     1663736.721      288986.406
#Sta/Elev= 30
       0  982.77     9.6  977.94    19.3  972.73    28.9   963.9    48.2  955.06
    57.9  950.79    67.5  946.64    86.8  938.75    96.5  934.64   106.1  927.68
   115.8  917.67     122  913.05   125.4  910.51   135.1   909.7     137  909.75
   144.7  909.97     164  911.36   212.2  914.17   221.9  915.09   231.5   915.8
   250.8  916.55   260.5  916.67   270.1  917.22   279.8  918.88   289.4  922.24
     299  927.58   308.7  937.65   318.3  948.08   337.6  962.04   356.9  975.83
#Mann= 3 , 0 , 0
       0     .06       0     122    .045       0     137     .06       0
Bank Sta=122,137
XS Rating Curve= 0 ,0
Exp/Cntr=0.3,0.1

Type RM Length L Ch R = 1 ,21653.1 ,328,320.6,313.2
XS GIS Cut Line= 2
     1663418.984      289436.532     1663728.875      289372.817
#Sta/Elev= 26
       0  952.13     9.6  945.94    19.2  939.17    28.8   932.6    38.4  928.39
    47.9  926.18    57.5  925.19    76.7  923.48    86.3  922.28    95.9  917.66
   105.5  909.79     115  904.02   122.4  902.74   124.6  902.36   134.2  904.62
   137.4  905.69   143.8  907.84   153.4  908.64   172.6  908.79   182.2  908.99
   201.3   909.2   230.1  910.02   239.7  910.53   268.4  911.14   306.8   911.6
   316.4   912.6
#Mann= 3 , 0 , 0
       0     .06       0   122.4    .045       0   137.4     .06       0
Bank Sta=122.4,137.4
XS Rating Curve= 0 ,0
Exp/Cntr=0.3,0.1

Type RM Length L Ch R = 1 ,21332.4 ,375.3,375.8,376.4
XS GIS Cut Line= 2
     1663591.704      289740.793     1663848.487      289590.234
#Sta/Elev= 24
       0  960.31     9.6  952.69    19.2  946.72    28.8  940.84    38.4  935.22
    57.6  924.57    67.2   915.9    76.8  907.89    84.5  903.02    86.4  901.82
      96  898.53    99.5  898.99   105.6   899.8   124.8  903.68   134.4  905.09
     144  905.72   172.8  906.01     192   906.4   211.2  907.06   230.4  907.28
   249.7  907.69   268.9   907.9   278.5  908.25   297.7  909.51
#Mann= 3 , 0 , 0
       0     .06       0    84.5    .045       0    99.5     .06       0
Bank Sta=84.5,99.5
XS Rating Curve= 0 ,0
Exp/Cntr=0.3,0.1

Type RM Length L Ch R = 1 ,20956.4 ,273.5,290.5,307.4
XS GIS Cut Line= 2
     1663813.396      290022.716     1664303.813      289749.744
#Sta/Elev= 30
       0   977.1     9.7  969.21    96.8   926.9   116.1  910.84   125.8  903.24
   135.7  896.42   145.2  894.77   150.7  895.26   174.2  899.77   183.9  900.44
   251.6  902.29     271  902.26     300  904.73   319.3  912.07     329  914.72
   338.7  918.26   348.4  923.83   367.7  940.95   377.4  947.87   387.1  953.16
   406.4  961.18   416.1  967.59   425.8  972.27   493.5 1000.48   503.2 1005.15
   512.9 1012.57   522.6 1018.37   532.2 1023.12   551.6 1030.59   561.3 1035.65
#Mann= 3 , 0 , 0
       0     .06       0   135.7    .045       0   150.7     .06       0
Bank Sta=135.7,150.7
XS Rating Curve= 0 ,0
Exp/Cntr=0.3,0.1

Type RM Length L Ch R = 1 ,20665.8 ,219.2,212.7,206.2
XS GIS Cut Line= 3
     1663854.067      290197.267     1664183.124      290270.082
     1664235.654      290281.706
#Sta/Elev= 30
       0  955.84     9.6  951.04    28.9  940.91    38.5  936.87    67.4     923
      77   917.2    86.7  902.22    96.3  895.41   105.9  892.61   134.8  888.74
   144.4  887.62   147.6  887.42   154.1     887   162.6  887.12   163.7  887.14
   173.3  888.55     183  891.21   192.6  893.06   202.2  893.09   211.8  893.32
   240.7  894.29   269.6  894.67   288.9  894.35   308.1  893.26   327.4  893.09
     337  893.16     346  893.38   372.9  894.32   381.8  895.15   390.8  898.15
#Mann= 3 , 0 , 0
       0     .06       0   147.6    .045       0   162.6     .06       0
Bank Sta=147.6,162.6
XS Rating Curve= 0 ,0
Exp/Cntr=0.3,0.1

Type RM Length L Ch R = 1 ,20453.1 ,364.5,354.5,344.6
XS GIS Cut Line= 2
     1663840.088      290447.896     1664176.736      290432.117
#Sta/Elev= 30
       0  895.59     9.6  895.02    28.9  894.59    48.2  895.19    67.4  894.86
    96.3  895.83   105.9  895.48   115.6  894.69   125.2  893.14   144.4   891.1
   154.1  888.89   163.7  885.67   173.3  883.12   181.8  882.51   192.6  882.38
   196.8  882.57   202.2  882.82   211.8  884.81   221.5  888.02   231.1  889.94
   250.4  890.63     260  891.25   269.6  893.09   279.2  896.56   288.9  901.89
   298.5  907.86   308.1  912.75   317.8  916.25   327.4  915.33     337  913.75
#Mann= 3 , 0 , 0
       0     .06       0   181.8    .045       0   196.8     .06       0
Bank Sta=181.8,196.8
XS Rating Curve= 0 ,0
Exp/Cntr=0.3,0.1

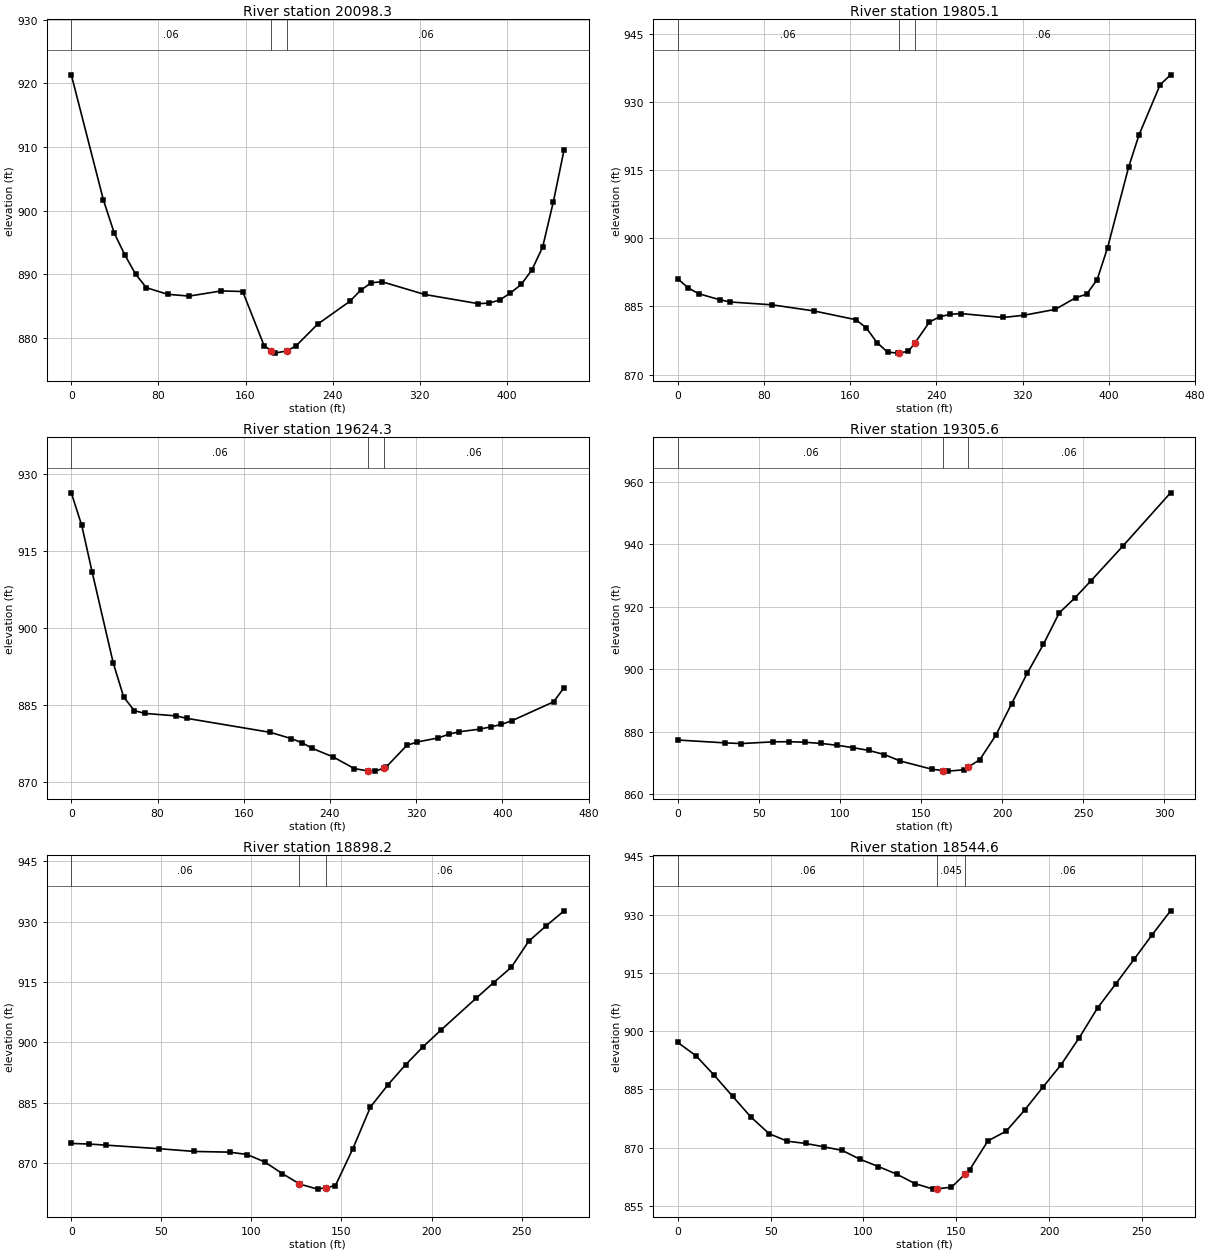
Type RM Length L Ch R = 1 ,20098.3 ,308.1,293,277.9
XS GIS Cut Line= 2
     1663956.948      290861.811     1664356.273       290648.99
#Sta/Elev= 30
       0  921.33    29.5  901.68    39.4  896.51    49.2  893.06      59  890.07
    68.9  887.93    88.5  886.89   108.2  886.61   137.7  887.42   157.4  887.33
   177.1  878.81   183.5  878.06   186.9  877.66   198.5  878.03   206.6  878.84
   226.2   882.2   255.8  885.79   265.6  887.51   275.4   888.7   285.3  888.86
   324.6  886.86   373.8  885.42   383.6  885.51   393.5  886.01   403.3   887.1
   413.2  888.44     423  890.73   432.8  894.28   442.7  901.43   452.5  909.55
#Mann= 3 , 0 , 0
       0     .06       0   183.5    .045       0   198.5     .06       0
Bank Sta=183.5,198.5
XS Rating Curve= 0 ,0
Exp/Cntr=0.3,0.1

Type RM Length L Ch R = 1 ,19805.1 ,173.2,180.9,188.5
XS GIS Cut Line= 2
     1664302.773      291058.179     1664494.455      290643.112
#Sta/Elev= 30
       0  891.08     9.7  889.06    19.4   887.8    38.9  886.47    48.6  885.98
    87.6  885.35   126.5     884   165.4  882.07   175.1  880.22   184.8  877.06
   194.6  874.96   204.3  874.73   205.1  874.76     214  875.12   220.1  876.99
   233.5  881.57   243.2  882.75   252.9  883.26   262.6  883.43   301.6  882.57
     321  883.05   350.2  884.35   369.6  886.96   379.4  887.68   389.1   890.9
   398.8  897.91   418.3  915.64     428  922.74   447.5  933.73   457.2  935.93
#Mann= 3 , 0 , 0
       0     .06       0   205.1    .045       0   220.1     .06       0
Bank Sta=205.1,220.1
XS Rating Curve= 0 ,0
Exp/Cntr=0.3,0.1

Type RM Length L Ch R = 1 ,19624.3 ,310.1,318.5,326.9
XS GIS Cut Line= 2
     1664354.544       291156.91     1664670.456      290826.423
#Sta/Elev= 30
       0  926.38     9.7  920.02    19.4  910.89    38.9  893.23    48.6   886.6
    58.4  883.96    68.1  883.41    97.3  882.92     107  882.45   184.8  879.71
   204.3  878.48     214   877.7   223.7  876.59   243.2   874.9   262.6  872.65
   275.2  872.21   282.1  872.16   290.2  872.76   291.8  872.88   311.3  877.17
     321  877.84   340.5  878.63   350.2  879.35   359.9  879.82   379.4  880.36
   389.1  880.78   398.8  881.25   408.6  881.96   447.5  885.66   457.2  888.44
#Mann= 3 , 0 , 0
       0     .06       0   275.2    .045       0   290.2     .06       0
Bank Sta=275.2,290.2
XS Rating Curve= 0 ,0
Exp/Cntr=0.3,0.1

Type RM Length L Ch R = 1 ,19305.6 ,405.2,407.3,409.4
XS GIS Cut Line= 2
     1664603.495      291240.109     1664879.422      291112.875
#Sta/Elev= 27
       0  877.37    29.4  876.45    39.2  876.24    58.8  876.79    68.6  876.83
    78.4  876.66    88.2  876.28      98   875.7   107.8  874.95   117.6  874.06
   127.4  872.72   137.2  870.65   156.8  868.02   163.8  867.59   166.6  867.42
   176.4  867.85   178.8  868.64   186.2  871.08     196  878.82   205.8  888.96
   215.6  898.87   225.4  907.97   235.2  918.05     245  922.92   254.8  928.34
   274.4  939.41   303.8  956.45
#Mann= 3 , 0 , 0
       0     .06       0   163.8    .045       0   178.8     .06       0
Bank Sta=163.8,178.8
XS Rating Curve= 0 ,0
Exp/Cntr=0.3,0.1

Type RM Length L Ch R = 1 ,18898.2 ,365.9,353.4,341
XS GIS Cut Line= 2
      1664801.28      291577.133      1665059.66      291487.219
#Sta/Elev= 26
       0  874.93     9.8  874.78    19.5   874.5    48.8  873.62    68.4  872.94
    87.9  872.77    97.7  872.18   107.5  870.31   117.2  867.43   126.5  864.95
     127  864.82   136.8  863.59   141.5  863.99   146.6  864.42   156.3  873.59
   166.1  883.97   175.9  889.53   185.6  894.46   195.4  898.96   205.2  903.05
   224.7  910.94   234.5  914.85   244.3  918.64     254  925.14   263.8  928.99
   273.6  932.66
#Mann= 3 , 0 , 0
       0     .06       0   126.5    .045       0   141.5     .06       0
Bank Sta=126.5,141.5
XS Rating Curve= 0 ,0
Exp/Cntr=0.3,0.1

Type RM Length L Ch R = 1 ,18544.6 ,642.5,650.7,659
XS GIS Cut Line= 2
     1665026.972      291938.232     1665195.453      291733.185
#Sta/Elev= 30
       0  897.06     9.8  893.65    19.7  888.58    29.5  883.22    39.3  877.91
    49.2  873.57      59  871.64    68.8  871.07    78.6   870.2    88.5  869.28
    98.3  866.96   108.1   865.1     118  863.14   127.8  860.72   137.6   859.3
   139.6   859.4   147.4  859.78   154.6   863.1   157.3  864.35   167.1  871.75
   176.9  874.22   186.8  879.64   196.6  885.52   206.4  891.31   216.2  898.25
   226.1  905.96   235.9  912.14   245.7  918.44   255.6  924.86   265.4  930.96
#Mann= 3 , 0 , 0
       0     .06       0   139.6    .045       0   154.6     .06       0
Bank Sta=139.6,154.6
XS Rating Curve= 0 ,0
Exp/Cntr=0.3,0.1

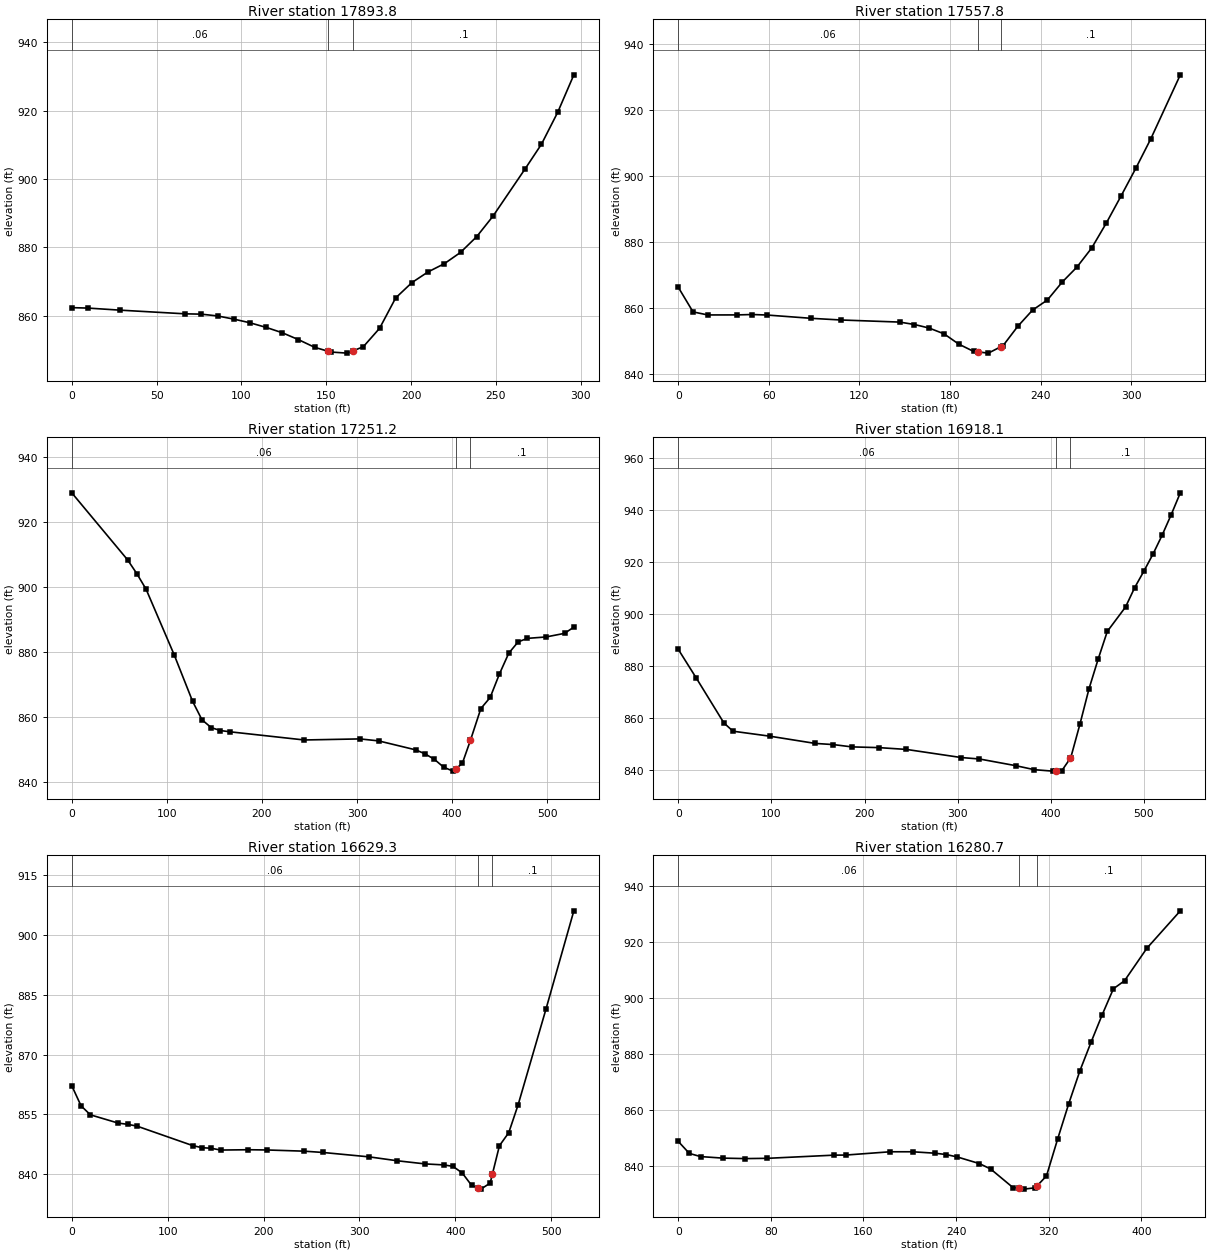
Type RM Length L Ch R = 1 ,17893.8 ,341.9,335.4,328.8
XS GIS Cut Line= 2
     1665446.192      292344.145     1665703.455      292197.902
#Sta/Elev= 29
       0  862.33     9.6   862.2    28.6  861.59    66.8  860.52    76.4  860.42
    85.9   859.9    95.5  858.97     105   857.9   114.6  856.54   124.1  854.97
   133.6  852.96   143.2   850.7   150.8   849.6   152.7  849.33   162.3  849.01
   165.8   849.7   171.8  850.87   181.4  856.27   190.9  865.18   200.5  869.68
     210   872.8   219.6  875.21   229.1   878.5   238.6   883.1   248.2  889.09
   267.3  903.06   276.8  910.18   286.4  919.55   295.9  930.51
#Mann= 3 , 0 , 0
       0     .06       0   150.8    .045       0   165.8      .1       0
Bank Sta=150.8,165.8
XS Rating Curve= 0 ,0
Exp/Cntr=0.3,0.1

Type RM Length L Ch R = 1 ,17557.8 ,311.5,306.4,301.3
XS GIS Cut Line= 2
     1665655.437      292665.382     1665885.986       292425.98
#Sta/Elev= 29
       0  866.31     9.8  858.84    19.6  857.92    39.1  857.93    48.9  858.05
    58.6   857.9      88   856.9   107.5   856.4   146.6  855.76   156.4  855.03
   166.2  853.94     176   852.2   185.7   849.1   195.5   846.9   198.4  846.74
   205.3  846.37   213.4  848.26   215.1  848.66   224.8  854.48   234.6   859.4
   244.4  862.44   254.2  867.86   263.9  872.37   273.7  878.15   283.5  885.79
   293.3  894.02     303  902.34   312.8  911.14   332.4  930.56
#Mann= 3 , 0 , 0
       0     .06       0   198.4    .045       0   213.4      .1       0
Bank Sta=198.4,213.4
XS Rating Curve= 0 ,0
Exp/Cntr=0.3,0.1

Type RM Length L Ch R = 1 ,17251.2 ,346.6,333.1,319.7
XS GIS Cut Line= 2
     1665838.547      293042.699     1666110.216      292589.917
#Sta/Elev= 30
       0  928.98    58.7  908.37    68.4  904.13    78.2  899.31   107.6  879.23
   127.1  864.83   136.9  859.19   146.7  856.76   156.4  855.87   166.2  855.49
   244.5  852.97   303.1   853.3   322.7  852.69   361.8  849.92   371.6  848.69
   381.4     847   391.1   844.6   400.9  843.39   404.2  844.19   410.7  845.76
   419.2  852.82   430.2  862.63     440  866.04   449.8  873.31   459.6  879.69
   469.4  883.13   479.1  884.22   498.7  884.65   518.2  885.76     528  887.67
#Mann= 3 , 0 , 0
       0     .06       0   404.2    .045       0   419.2      .1       0
Bank Sta=404.2,419.2
XS Rating Curve= 0 ,0
Exp/Cntr=0.3,0.1

Type RM Length L Ch R = 1 ,16918.1 ,282.3,288.7,295.1
XS GIS Cut Line= 2
     1666392.839      293160.425     1666362.557      292622.254
#Sta/Elev= 30
       0  886.31    19.6  875.12      49  857.98    58.8   854.8      98   852.9
     147   850.1   166.6  849.65   186.2  848.77   215.6  848.48     245  847.79
   303.8  844.67   323.4  844.11   362.6  841.52   382.2     840   401.8  839.44
   405.8  839.47   411.6  839.52   420.8  844.31   421.4  844.62   431.2  857.45
     441  871.15   450.8  882.53   460.6  893.18   480.2  902.58     490  910.03
   499.8  916.32   509.6  922.88   519.4  930.15   529.2  938.09     539  946.51
#Mann= 3 , 0 , 0
       0     .06       0   405.8    .045       0   420.8      .1       0
Bank Sta=405.8,420.8
XS Rating Curve= 0 ,0
Exp/Cntr=0.3,0.1

Type RM Length L Ch R = 1 ,16629.3 ,348,348.7,349.4
XS GIS Cut Line= 2
     1666559.999      293160.313     1666678.817      292650.293
#Sta/Elev= 30
       0   862.2     9.7  857.16    19.4  854.91    48.5  852.83    58.2  852.53
    67.9  852.09   126.1   847.2   135.8  846.67   145.5  846.53   155.2  846.08
   184.3  846.16   203.6   846.1   242.4   845.8   261.8  845.48   310.3  844.37
   339.4   843.4   368.5  842.61   387.9  842.36   397.6     842   407.3  840.33
     417  837.25   423.7  836.59   426.7  836.29   436.4   837.8   438.7  840.02
   446.1  847.18   455.8  850.43   465.5  857.36   494.6  881.37   523.7  906.02
#Mann= 3 , 0 , 0
       0     .06       0   423.7    .045       0   438.7      .1       0
Bank Sta=423.7,438.7
XS Rating Curve= 0 ,0
Exp/Cntr=0.3,0.1

Type RM Length L Ch R = 1 ,16280.7 ,692.8,688.9,684.9
XS GIS Cut Line= 2
     1666917.088      293110.365     1667030.248      292691.672
#Sta/Elev= 30
       0  848.65     9.6  844.35    19.3  843.22    38.6  842.67    57.8   842.5
    77.1   842.6   134.9  843.74   144.6  843.76   183.1  844.94   202.4  844.94
   221.7  844.43   231.3  843.96     241  843.09   260.2  840.71   269.9  838.77
   289.1  832.16   294.6  831.84   298.8  831.59   308.4  832.08   309.6   832.6
   318.1  836.31   327.7  849.44   337.3  862.09     347  873.92   356.6   884.1
   366.2  893.88   375.9  903.19   385.5  906.05   404.8  917.66   433.7  931.04
#Mann= 3 , 0 , 0
       0     .06       0   294.6    .045       0   309.6      .1       0
Bank Sta=294.6,309.6
XS Rating Curve= 0 ,0
Exp/Cntr=0.3,0.1