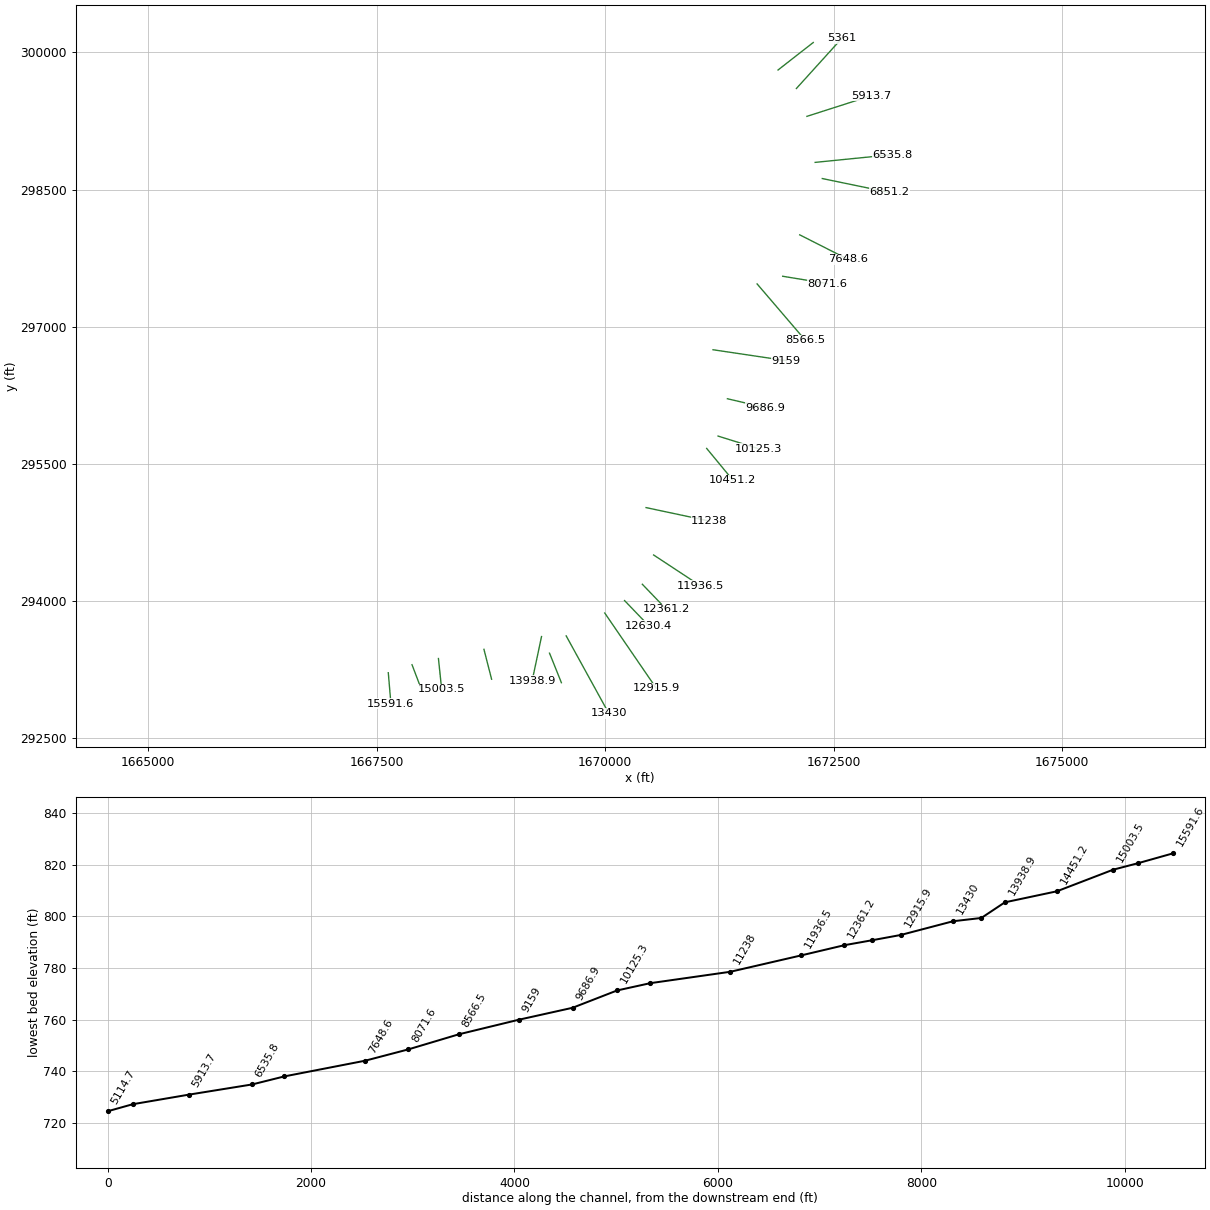
HEC-RAS study WHITMANCRK.prj: WHITMANCRK

--- WHITMANCRK.g01 (geometry) --- (continued)

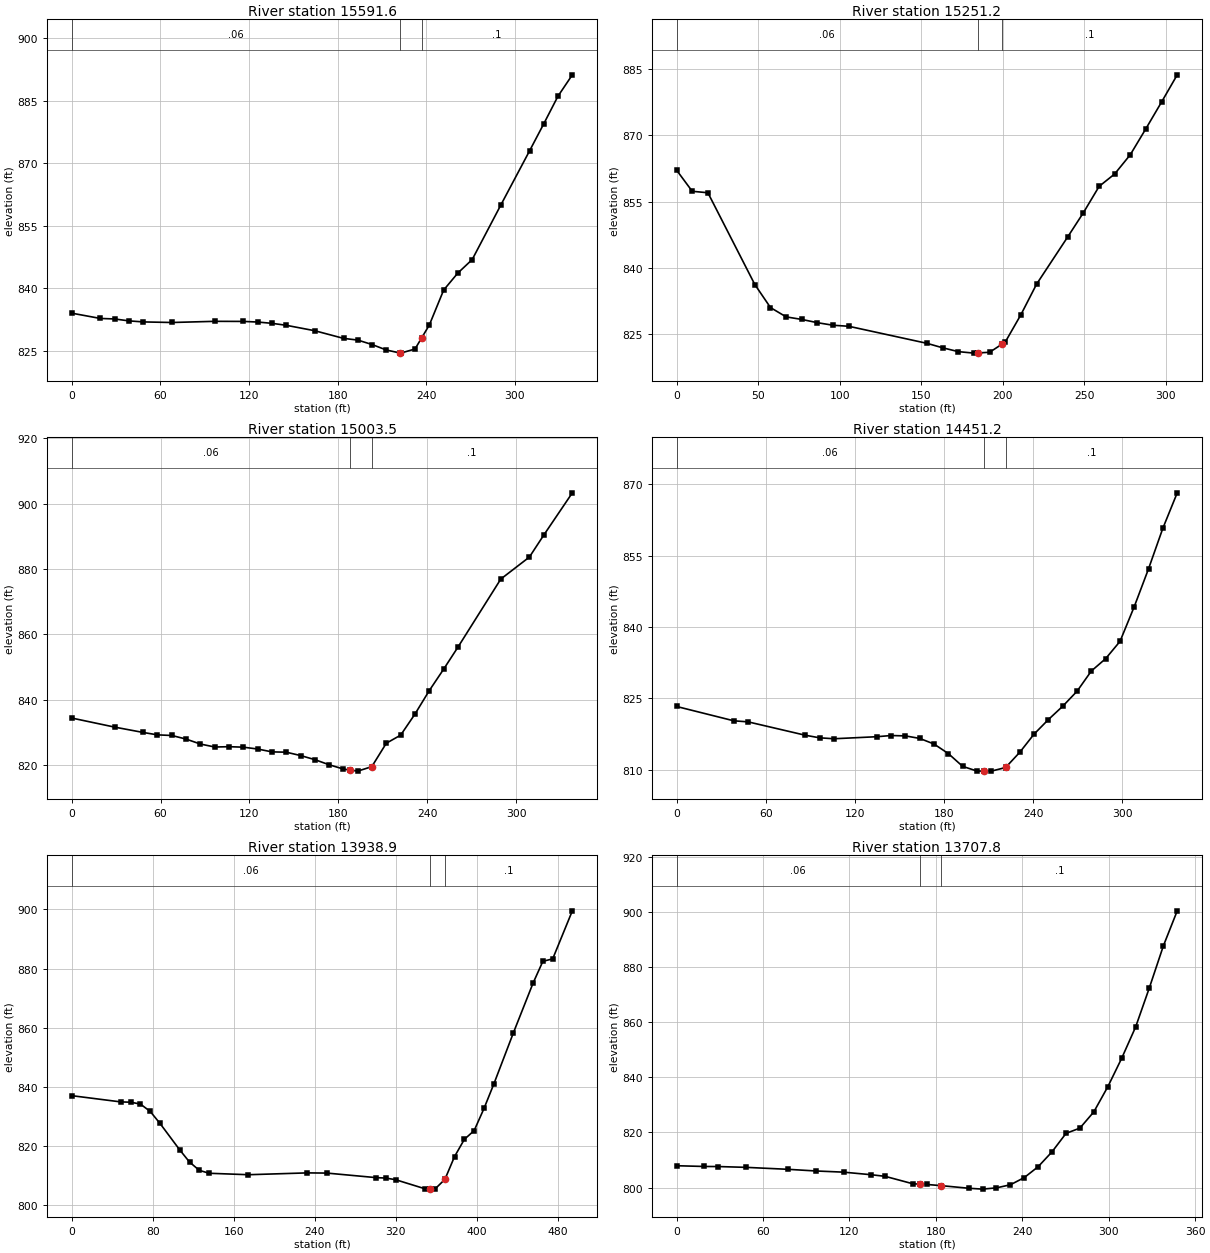
Type RM Length L Ch R = 1 ,15591.6 ,334,340.3,346.6
XS GIS Cut Line= 2
     1667626.917      293216.858     1667655.707      292879.163
#Sta/Elev= 29
       0     834    19.4  832.73      29  832.61    38.7  832.15    48.4   831.9
    67.8  831.76    96.8  832.04   116.2  832.02   125.9  831.87   135.6  831.56
   145.2  831.09   164.6  829.78     184  827.95   193.7  827.54   203.4  826.46
     213  825.16     222  824.46   222.7  824.41   232.4   825.4     237  828.13
   242.1  831.16   251.8  839.55   261.4  843.63   271.1  846.86   290.5  859.96
   309.9  872.92   319.6  879.47   329.2  886.08   338.9  891.19
#Mann= 3 , 0 , 0
       0     .06       0     222    .045       0     237      .1       0
Bank Sta=222,237
XS Rating Curve= 0 ,0
Exp/Cntr=0.3,0.1

Type RM Length L Ch R = 1 ,15251.2 ,253.4,247.6,241.8
XS GIS Cut Line= 2
     1667886.554        293304.9     1667995.654      293017.795
#Sta/Elev= 28
       0  862.13     9.6  857.34    19.2  857.01      48  836.19    57.6  830.97
    67.2  828.86    76.8  828.28    86.4  827.54      96  826.96   105.6  826.73
   153.6  822.86   163.2  821.85   172.8  820.98   182.4  820.64   184.8  820.69
     192  820.83   199.8  822.72   201.6  823.15   211.2  829.35   220.8  836.27
     240  847.04   249.6  852.52   259.2  858.46   268.7  861.26   278.3  865.63
   287.9  871.55   297.5  877.59   307.1  883.75
#Mann= 3 , 0 , 0
       0     .06       0   184.8    .045       0   199.8      .1       0
Bank Sta=184.8,199.8
XS Rating Curve= 0 ,0
Exp/Cntr=0.3,0.1

Type RM Length L Ch R = 1 ,15003.5 ,548.8,552.2,555.7
XS GIS Cut Line= 2
     1668175.632      293372.505     1668210.757      293036.375
#Sta/Elev= 30
       0  834.34      29  831.56    48.3  829.92    57.9  829.19    67.6     829
    77.2   827.9    86.9  826.38    96.6  825.47   106.2  825.57   115.9  825.42
   125.5  824.86   135.2  823.98   144.8  823.89   154.5  822.86   164.2   821.6
   173.8  820.04   183.5  818.72   187.6  818.45   193.1  818.09   202.6  819.46
   212.4  826.63   222.1  829.11   231.7  835.52   241.4  842.73   251.1  849.29
   260.7  855.99   289.7  876.88     309  883.61   318.6  890.26     338  903.27
#Mann= 3 , 0 , 0
       0     .06       0   187.6    .045       0   202.6      .1       0
Bank Sta=187.6,202.6
XS Rating Curve= 0 ,0
Exp/Cntr=0.3,0.1

Type RM Length L Ch R = 1 ,14451.2 ,522.5,512.1,501.8
XS GIS Cut Line= 2
     1668673.556      293472.529     1668757.226      293146.217
#Sta/Elev= 30
       0  823.32    38.5  820.31    48.1  820.09    86.6  817.28    96.2  816.74
   105.9  816.54   134.8  816.97   144.4  817.22     154  817.14   163.6  816.61
   173.2  815.44   182.9  813.42   192.5  810.74   202.1  809.76   206.8  809.75
   211.8  809.74   221.4   810.5   221.8  810.63     231  813.72   240.6  817.53
   250.2  820.57   259.9  823.39   269.5  826.53   279.1  830.77   288.7  833.36
   298.4     837     308  844.31   317.6  852.25   327.2  860.74   336.9   868.2
#Mann= 3 , 0 , 0
       0     .06       0   206.8    .045       0   221.8      .1       0
Bank Sta=206.8,221.8
XS Rating Curve= 0 ,0
Exp/Cntr=0.3,0.1

Type RM Length L Ch R = 1 ,13938.9 ,217.6,231,244.4
XS GIS Cut Line= 2
     1669303.438      293612.587     1669200.962       293129.12
#Sta/Elev= 30
       0  837.05    48.4  834.94    58.1  834.84    67.8  834.22    77.5  831.72
    87.2  827.65   106.6  818.74   116.3  814.62     126   811.8   135.7  810.82
   174.4  810.33   232.6  810.95     252  810.88   300.4  809.35   310.1   809.2
   319.8  808.64   348.8  805.57   353.4  805.52   358.5  805.46   368.4  808.76
   377.9  816.45   387.6  822.28   397.3  825.26     407  832.73   416.7  840.99
   436.1  858.37   455.4  875.07   465.1  882.46   474.8  883.28   494.2  899.52
#Mann= 3 , 0 , 0
       0     .06       0   353.4    .045       0   368.4      .1       0
Bank Sta=353.4,368.4
XS Rating Curve= 0 ,0
Exp/Cntr=0.3,0.1

Type RM Length L Ch R = 1 ,13707.8 ,275.7,278.2,280.6
XS GIS Cut Line= 2
     1669390.939      293430.997     1669520.767      293108.499
#Sta/Elev= 29
       0   807.9    19.3  807.63      29   807.6    48.3  807.31    77.3   806.6
    96.6     806   115.9  805.57   135.2  804.63   144.8  804.05   164.2  801.33
   168.8  801.22   173.8   801.1   183.8  800.67   202.8  799.73   212.4  799.41
   222.1  799.87   231.8     801   241.4   803.6   251.1  807.58   260.7  812.97
   270.4  819.65     280  821.54   289.7  827.45   299.4  836.56     309  846.85
   318.7  858.23   328.3  872.54     338  887.71   347.6  900.39
#Mann= 3 , 0 , 0
       0     .06       0   168.8    .045       0   183.8      .1       0
Bank Sta=168.8,183.8
XS Rating Curve= 0 ,0
Exp/Cntr=0.3,0.1

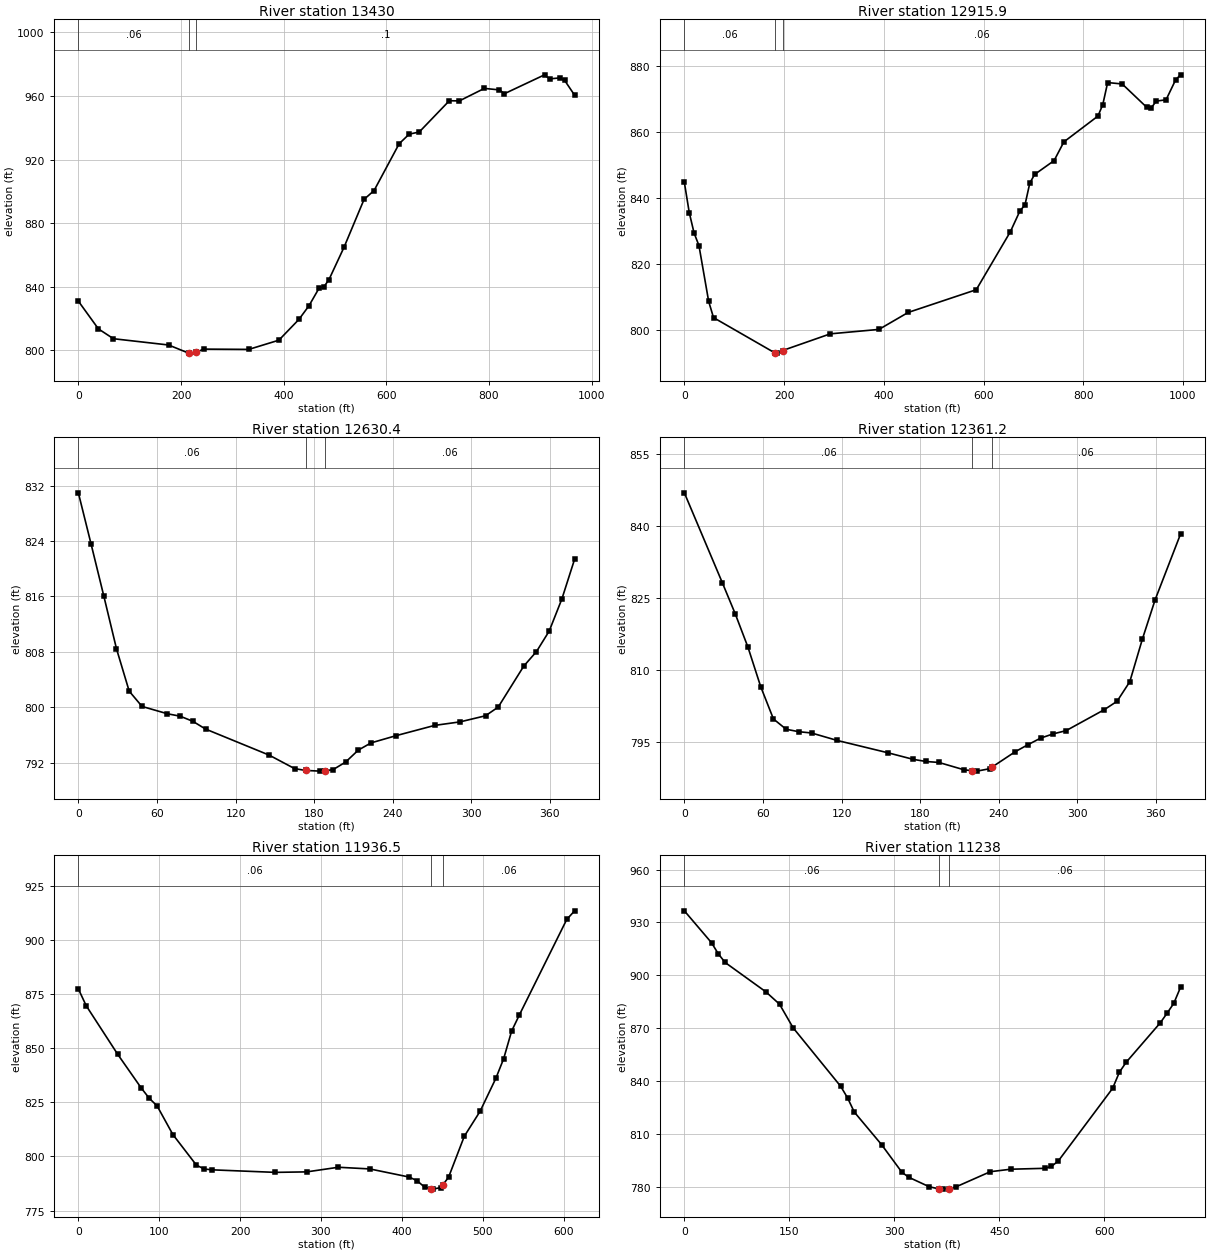
Type RM Length L Ch R = 1 ,13430   ,511.2,513.7,516.2
XS GIS Cut Line= 2
     1669573.233      293619.795     1670039.676      292772.823
#Sta/Elev= 30
       0  830.87    39.1  813.39    68.4  807.21   175.8  803.26   214.9  798.14
   229.9  798.75   244.2  800.67   332.1  800.49   390.7  806.29   429.7  819.35
   449.3  827.93   468.8  838.92   478.6  839.97   488.3  844.43   517.6  864.76
   556.7  894.94   576.2   900.5   625.1  929.98   644.6     936   664.2  937.34
   722.8  957.03   742.3  956.92   791.1   964.8   820.4  963.85   830.2  961.46
   908.3  973.34   918.1  970.79   937.6  971.38   947.4  969.88   966.9  960.52
#Mann= 3 , 0 , 0
       0     .06       0   214.9    .045       0   229.9      .1       0
Bank Sta=214.9,229.9
XS Rating Curve= 0 ,0
Exp/Cntr=0.3,0.1

Type RM Length L Ch R = 1 ,12915.9 ,281.7,285.4,289.2
XS GIS Cut Line= 2
     1669995.007      293870.063     1670557.838      293049.267
#Sta/Elev= 30
       0  844.73     9.8  835.56    19.5  829.33    29.3   825.5    48.8  808.52
    58.5  803.62     182  792.86   185.4  792.83     197  793.62   292.7  798.69
   390.3  800.04   448.8  805.19   585.4   812.1   653.7  829.69   673.2  836.12
     683  837.81   692.8  844.52   702.5  847.13   741.5  851.33   761.1  857.02
   829.4  864.86   839.1  868.33   848.9  875.05   878.1  874.62   926.9  867.58
   936.7  867.42   946.4  869.42     966   869.8   985.5  875.96   995.2   877.4
#Mann= 3 , 0 , 0
       0     .06       0     182    .045       0     197     .06       0
Bank Sta=182,197
XS Rating Curve= 0 ,0
Exp/Cntr=0.3,0.1

Type RM Length L Ch R = 1 ,12630.4 ,269.4,269.4,269.5
XS GIS Cut Line= 2
     1670211.831       294006.17     1670474.436      293733.137
#Sta/Elev= 29
       0  830.98     9.7  823.59    19.4  816.09    29.1  808.45    38.8  802.32
    48.6  800.11      68  799.05    77.7   798.7    87.4  797.96    97.1  796.84
   145.7  793.07   165.1  791.12   173.5  790.86   184.6  790.76   188.5  790.84
   194.3  790.96     204  792.07   213.7   793.8   223.4  794.84   242.8   795.9
     272  797.37   291.4  797.88   310.8  798.76   320.5  800.02     340  805.94
   349.7  808.04   359.4     811   369.1  815.65   378.8  821.39
#Mann= 3 , 0 , 0
       0     .06       0   173.5    .045       0   188.5     .06       0
Bank Sta=173.5,188.5
XS Rating Curve= 0 ,0
Exp/Cntr=0.3,0.1

Type RM Length L Ch R = 1 ,12361.2 ,419.5,424.4,429.4
XS GIS Cut Line= 2
     1670406.313      294184.484     1670668.917      293911.451
#Sta/Elev= 30
       0  846.97    29.1  828.13    38.8  821.74    48.6  814.71    58.3  806.49
      68  799.76    77.7  797.61    87.4   797.1    97.1  796.83   116.6  795.28
   155.4   792.7   174.8  791.32   184.6  790.88   194.3  790.68   213.7  789.13
   219.8  788.97   223.4  788.87   233.1  789.38   234.8   789.7   252.6  792.93
   262.3  794.39     272  795.77   281.7  796.66   291.4  797.32   320.5  801.69
   330.3  803.45     340  807.53   349.7   816.5   359.4  824.68   378.8   838.4
#Mann= 3 , 0 , 0
       0     .06       0   219.8    .045       0   234.8     .06       0
Bank Sta=219.8,234.8
XS Rating Curve= 0 ,0
Exp/Cntr=0.3,0.1

Type RM Length L Ch R = 1 ,11936.5 ,689.9,698,706.1
XS GIS Cut Line= 2
     1670529.887      294504.498     1671042.578      294167.202
#Sta/Elev= 30
       0   877.4     9.7  869.64    48.7  847.17    77.9  831.56    87.7  826.88
    97.4  823.35   116.9  810.13   146.1  795.95   155.9   794.2   165.6  793.83
   243.5  792.66   282.5  792.89   321.5  795.02   360.4  794.25   409.1   790.5
   418.9   788.8   428.6   785.7   435.7  785.13   438.4  784.92   448.1  785.62
   450.7   786.9   457.8  790.38   477.3  809.34   496.8  820.86   516.3  836.09
     526  845.21   535.8  857.91   545.5  865.47     604  909.49   613.7  913.47
#Mann= 3 , 0 , 0
       0     .06       0   435.7    .045       0   450.7     .06       0
Bank Sta=435.7,450.7
XS Rating Curve= 0 ,0
Exp/Cntr=0.3,0.1

Type RM Length L Ch R = 1 ,11238   ,801.4,786.9,772.3
XS GIS Cut Line= 2
     1670446.998      295022.533     1671140.253      294875.187
#Sta/Elev= 30
       0  936.55    38.8  918.44    48.5  912.14    58.2  907.24   116.5  890.54
   135.9  883.56   155.3  870.16   223.3  836.91     233  830.42   242.7  822.32
   281.6  803.85   310.7  788.14   320.4  785.32   349.5  779.96     363  778.73
   368.9  778.57     378   778.8   388.4  779.94   436.9  788.46     466  789.87
   514.6  790.38   524.3  791.48     534  794.54   611.6  835.78   621.4  845.04
   631.1  850.64   679.6  872.94   689.3  878.37     699  884.06   708.7  893.25
#Mann= 3 , 0 , 0
       0     .06       0     363    .045       0     378     .06       0
Bank Sta=363,378
XS Rating Curve= 0 ,0
Exp/Cntr=0.3,0.1

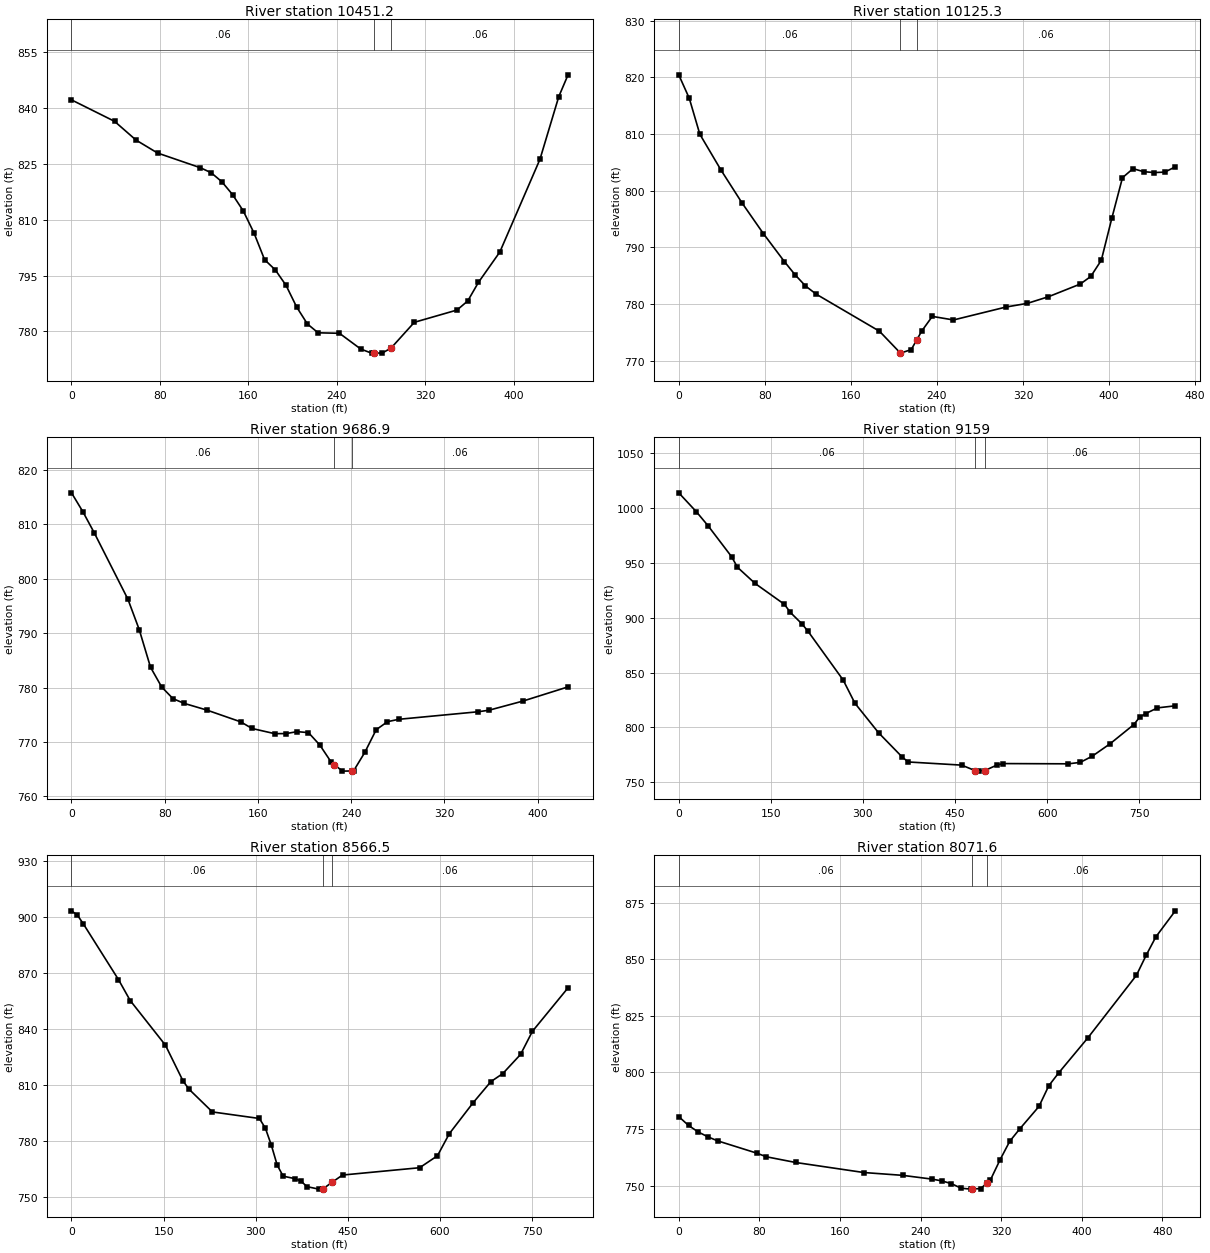
Type RM Length L Ch R = 1 ,10451.2 ,312.8,325.9,339
XS GIS Cut Line= 4
     1671110.304      295669.442      1671178.42      295586.971
     1671369.249      295355.925     1671396.256      295323.228
#Sta/Elev= 30
       0  842.21    38.9  836.45    58.3  831.42    77.8  827.93   116.6  823.97
   126.3  822.63     136   820.2   145.6  816.77   155.3  812.39     165  806.46
   174.6  799.27   184.3  796.52     194  792.37   203.6  786.55   213.3     782
     223  779.62   242.3  779.49   261.6  775.25   271.3  774.16   273.9  774.17
     281  774.19   288.9   775.5     310  782.44   348.6  785.74   358.3  788.18
     368  793.18   387.3  801.32   423.6  826.24   440.6  843.07     449  848.94
#Mann= 3 , 0 , 0
       0     .06       0   273.9    .045       0   288.9     .06       0
Bank Sta=273.9,288.9
XS Rating Curve= 0 ,0
Exp/Cntr=0.3,0.1

Type RM Length L Ch R = 1 ,10125.3 ,436.6,438.3,439.9
XS GIS Cut Line= 2
     1671235.046      295804.403       1671675.7      295666.962
#Sta/Elev= 30
       0  820.43     9.8  816.28    19.6  809.95    39.3  803.62    58.9  797.81
    78.6  792.44    98.2  787.49     108  785.19   117.8  783.19   127.7  781.75
   186.6   775.2   206.1  771.34   216.1  771.96   221.1  773.63   225.9  775.24
   235.7  777.82   255.4  777.19   304.4  779.48   324.1  780.12   343.7  781.29
   373.2  783.52     383  784.86   392.8  787.72   402.7  795.22   412.5  802.29
   422.3  803.88   432.1  803.35     442  803.19   451.8  803.27   461.6   804.2
#Mann= 3 , 0 , 0
       0     .06       0   206.1    .045       0   221.1     .06       0
Bank Sta=206.1,221.1
XS Rating Curve= 0 ,0
Exp/Cntr=0.3,0.1

Type RM Length L Ch R = 1 ,9686.9  ,525.9,527.8,529.6
XS GIS Cut Line= 2
     1671337.225      296212.473     1671752.096      296115.739
#Sta/Elev= 30
       0   815.8     9.7  812.35    19.4   808.5    48.4  796.24    58.1  790.66
    67.8  783.73    77.4  780.09    87.1  777.95    96.8  777.08   116.2  775.85
   145.2  773.69   154.9  772.47   174.3  771.52     184  771.53   193.6  771.89
   203.3  771.71     213  769.44   222.7  766.32   225.5  765.83   232.4  764.63
   240.5  764.66     242  764.67   251.7   768.1   261.4  772.24   271.1  773.72
   280.8  774.16   348.6  775.54   358.2  775.83   387.3  777.51     426  780.12
#Mann= 3 , 0 , 0
       0     .06       0   225.5    .045       0   240.5     .06       0
Bank Sta=225.5,240.5
XS Rating Curve= 0 ,0
Exp/Cntr=0.3,0.1

Type RM Length L Ch R = 1 ,9159    ,608.3,592.5,576.6
XS GIS Cut Line= 3
     1671179.716      296748.225     1671482.409      296703.212
     1671979.631      296629.273
#Sta/Elev= 30
       0 1013.99    28.7  996.71    47.8  983.88    86.1  955.67    95.6  946.04
   124.3   931.3   172.1  912.22   181.7  904.88   200.8   894.3   210.4  887.74
   267.8  843.11   286.9  821.98   325.4  795.03     364  772.83   373.7  768.37
   460.7  765.49   483.2  760.37   489.7  760.01   498.2  760.47   518.7   765.7
   528.4   766.9   634.7  766.68     654  768.01   673.4  773.64   702.4  784.94
     741  802.42   750.7  809.25   760.4   812.5   779.7  817.74   808.7  819.62
#Mann= 3 , 0 , 0
       0     .06       0   483.2    .045       0   498.2     .06       0
Bank Sta=483.2,498.2
XS Rating Curve= 0 ,0
Exp/Cntr=0.3,0.1

Type RM Length L Ch R = 1 ,8566.5  ,479,494.6,510.3
XS GIS Cut Line= 3
     1671662.011      297468.115     1671861.051      297235.667
     1672188.006      296853.832
#Sta/Elev= 30
       0  903.18     9.6  900.89    19.1   896.3    76.5  866.41    95.6  855.21
     153  831.32   181.7  812.15   191.3  807.81   229.5  795.62     306  792.12
   315.7  786.99   325.4  777.95     335   767.2   344.7  761.28     364  759.94
   373.7  758.68   383.4  755.68   402.7  754.34   409.9  754.56   424.9  758.12
   441.4  761.87     567  765.79     596  772.18   615.4  784.02     654   800.5
     683  811.82   702.4  816.13   731.4  826.39   750.7  838.75   808.7     862
#Mann= 3 , 0 , 0
       0     .06       0   409.9    .045       0   424.9     .06       0
Bank Sta=409.9,424.9
XS Rating Curve= 0 ,0
Exp/Cntr=0.3,0.1

Type RM Length L Ch R = 1 ,8071.6  ,430,423,416
XS GIS Cut Line= 2
     1671942.036      297551.559     1672428.416      297472.192
#Sta/Elev= 30
       0  780.53     9.7  776.63    19.3  773.75      29  771.58    38.6  769.82
    77.3  764.42      87  762.79     116  760.28   183.6  755.85   222.2   754.6
   251.2  752.95   260.9  752.17   270.6  750.95   280.2  748.92   289.9  748.52
     291  748.55   299.6  748.77     306  751.23   309.2  752.46   318.9  761.49
   328.5  769.64   338.2  774.98   357.5  785.01   367.2  794.12   376.9  799.73
   405.8  815.16   454.2  842.88   463.8  851.66   473.5  859.84   492.8  871.34
#Mann= 3 , 0 , 0
       0     .06       0     291    .045       0     306     .06       0
Bank Sta=291,306
XS Rating Curve= 0 ,0
Exp/Cntr=0.3,0.1

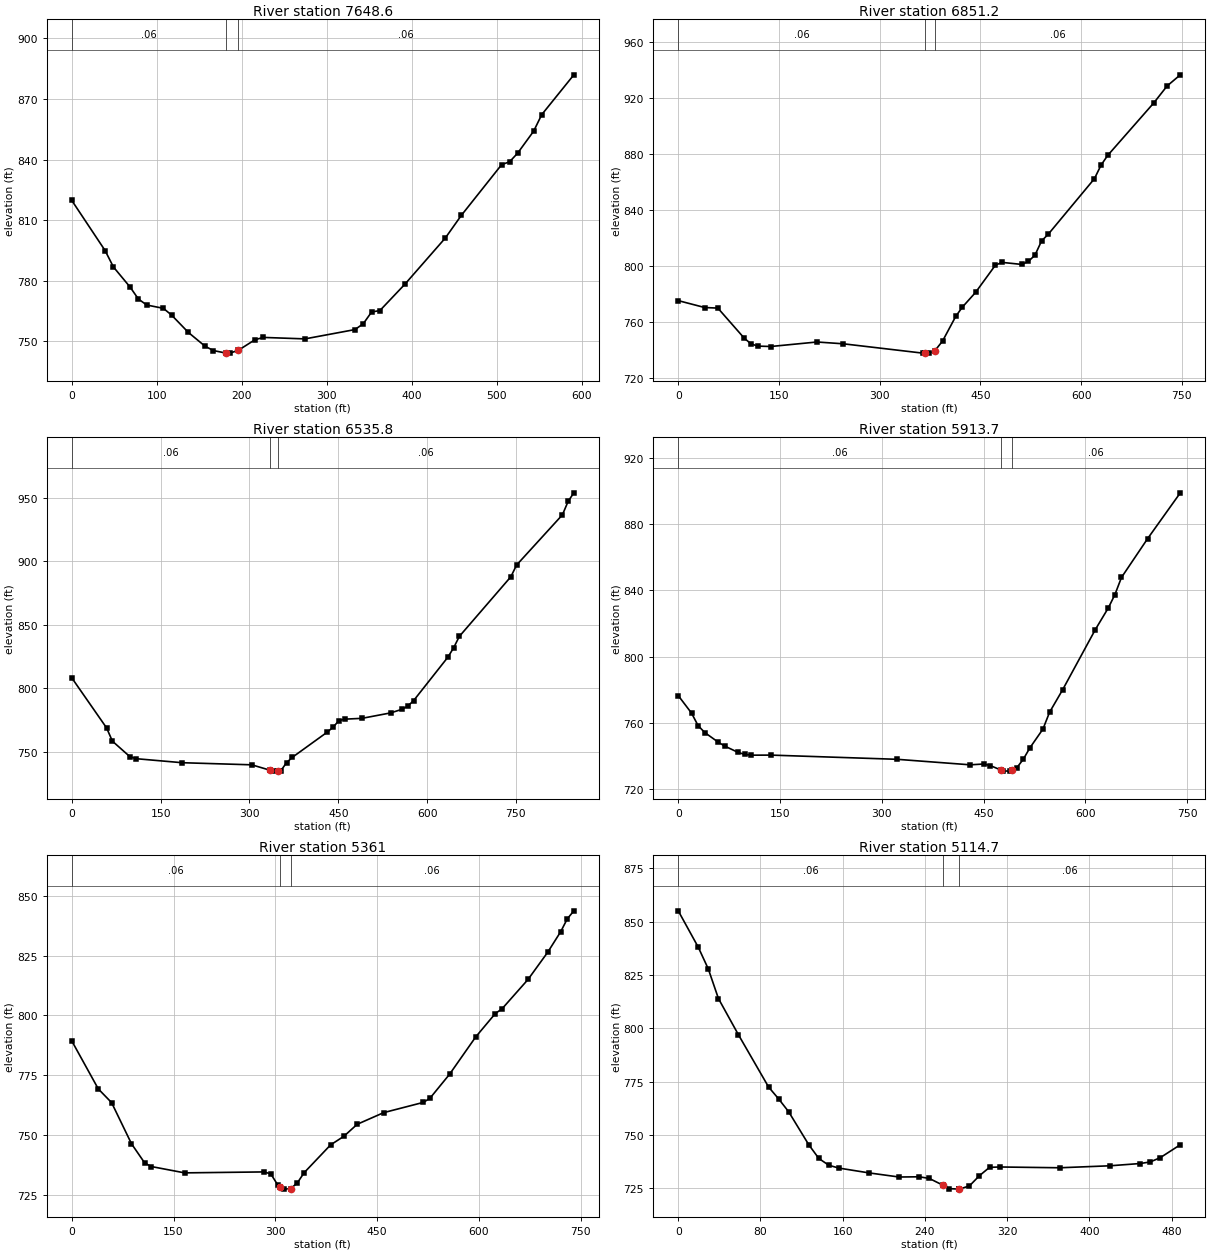
Type RM Length L Ch R = 1 ,7648.6  ,791.1,797.1,803.1
XS GIS Cut Line= 3
      1672128.57      298004.329     1672487.021      297822.745
     1672655.587      297737.353
#Sta/Elev= 30
       0  819.77    39.2  794.96      49  786.82    68.6  776.88    78.4  770.95
    88.2  767.97   107.8  766.34   117.6  762.93   137.2   754.4   156.8  747.58
   166.6  745.43   181.1   744.2   186.2  744.15   196.1  745.58   215.6  750.79
   225.4  751.93   274.4   751.2   333.2  755.81     343   758.7   352.8  764.51
   362.6  765.24     392  778.28   439.6  801.18   458.5  812.42   505.8  837.47
   515.2  838.92   524.6  843.15   543.5  854.07     553  862.25   590.8  881.97
#Mann= 3 , 0 , 0
       0     .06       0   181.1    .045       0   196.1     .06       0
Bank Sta=181.1,196.1
XS Rating Curve= 0 ,0
Exp/Cntr=0.3,0.1

Type RM Length L Ch R = 1 ,6851.2  ,308.3,315.2,322.1
XS GIS Cut Line= 2
     1672375.327      298619.834     1673107.648      298468.425
#Sta/Elev= 30
       0  775.45    39.4  770.53      59  770.13    98.4  748.66   108.2  744.74
   118.1  743.06   137.8  742.77   206.6  745.98     246  744.69   364.1  738.05
   367.3  738.08   373.9  738.15   382.3  739.82   393.6  746.58   413.3   764.2
   423.1  770.77   442.8  781.27   472.3  800.64   482.1   802.7   511.7  801.22
   521.5  803.37   531.3  807.81   541.2  818.01     551  822.68   619.9  862.31
   629.7  871.93   639.6  878.86   708.4  916.33   728.1  928.33   747.8  936.28
#Mann= 3 , 0 , 0
       0     .06       0   367.3    .045       0   382.3     .06       0
Bank Sta=367.3,382.3
XS Rating Curve= 0 ,0
Exp/Cntr=0.3,0.1

Type RM Length L Ch R = 1 ,6535.8  ,617.3,622,626.7
XS GIS Cut Line= 3
     1672297.449      298796.697     1672765.809      298843.681
     1673141.043      298881.324
#Sta/Elev= 30
       0   808.3    58.8  768.94    68.6  758.52    98.1  746.34   107.9  744.76
   186.3  741.57     304  739.91     334  735.77   343.2  734.95     349  735.12
     353  735.24   362.8   741.7   372.6  745.86   431.5  765.65   441.3  769.51
   451.1  774.69   460.9  775.81     490  776.46   538.4  780.73   557.7  783.58
   567.4  786.11   577.1  790.32   635.1  824.55   644.8  831.92   654.4  840.87
   741.5  887.84   751.1     897   828.5   936.5   838.2  947.14   847.8  953.79
#Mann= 3 , 0 , 0
       0     .06       0     334    .045       0     349     .06       0
Bank Sta=334,349
XS Rating Curve= 0 ,0
Exp/Cntr=0.3,0.1

Type RM Length L Ch R = 1 ,5913.7  ,541,552.6,564.3
XS GIS Cut Line= 3
     1672207.309      299299.902     1672691.735      299454.831
     1672912.035      299525.287
#Sta/Elev= 30
       0  776.54    19.6  765.99    29.3   758.4    39.1  754.27    58.7  748.53
    68.5   746.1      88  742.33    97.8  741.09   107.6  740.62   136.9  740.66
   322.8  738.12   430.4   734.8   449.9  735.29   459.7  734.38   476.2  731.54
   479.3  731.11     489     731   491.2  731.44   498.8  732.94   508.6  738.22
   518.2  745.02   537.5  756.38   547.2  766.48   566.4     780   614.6  816.29
   633.9  829.47   643.5  837.42   653.2  847.77   691.7  871.16   739.9  898.78
#Mann= 3 , 0 , 0
       0     .06       0   476.2    .045       0   491.2     .06       0
Bank Sta=476.2,491.2
XS Rating Curve= 0 ,0
Exp/Cntr=0.3,0.1

Type RM Length L Ch R = 1 ,5361    ,249.8,246.1,242.3
XS GIS Cut Line= 3
     1672092.115       299604.54     1672433.692      299981.364
      1672589.03       300152.73
#Sta/Elev= 30
       0  789.29    39.1   769.2    58.7  763.47      88  746.27   107.6  738.18
   117.4  736.73   166.3  734.09   283.6  734.49   293.4  733.62   303.2  729.18
   307.5  728.35     313  727.29   322.5  727.47   332.5  729.92   342.3  734.12
   381.4  745.79     401  749.39   420.6  754.41   459.7  759.29   518.2  763.58
   527.9  765.32   556.8  775.36   595.3  790.96   624.2  800.75   633.9  802.66
   672.4     815   701.3  826.34   720.6  835.01   730.2  840.33   739.9   843.7
#Mann= 3 , 0 , 0
       0     .06       0   307.5    .045       0   322.5     .06       0
Bank Sta=307.5,322.5
XS Rating Curve= 0 ,0
Exp/Cntr=0.3,0.1

Type RM Length L Ch R = 1 ,5114.7  ,234.2,234.8,235.5
XS GIS Cut Line= 2
     1671891.186      299806.674      1672276.25      300107.133
#Sta/Elev= 30
       0  855.12    19.5  838.04    29.3  827.79    39.1  813.97    58.6  796.95
    87.9  772.46    97.7  766.88   107.4  760.88     127  745.38   136.8  738.94
   146.5  735.76   156.3  734.44   185.6  732.18   214.9  730.25   234.4  730.36
   244.2  729.59   257.7  726.36   263.7   724.8   272.7  724.59   273.5  724.57
   283.3  726.11     293  730.88   302.8  734.78   312.6  734.96   371.2  734.59
     420  735.52   449.3  736.58   459.1  737.31   468.9  739.33   488.4  745.39
#Mann= 3 , 0 , 0
       0     .06       0   257.7    .045       0   272.7     .06       0
Bank Sta=257.7,272.7
XS Rating Curve= 0 ,0
Exp/Cntr=0.3,0.1