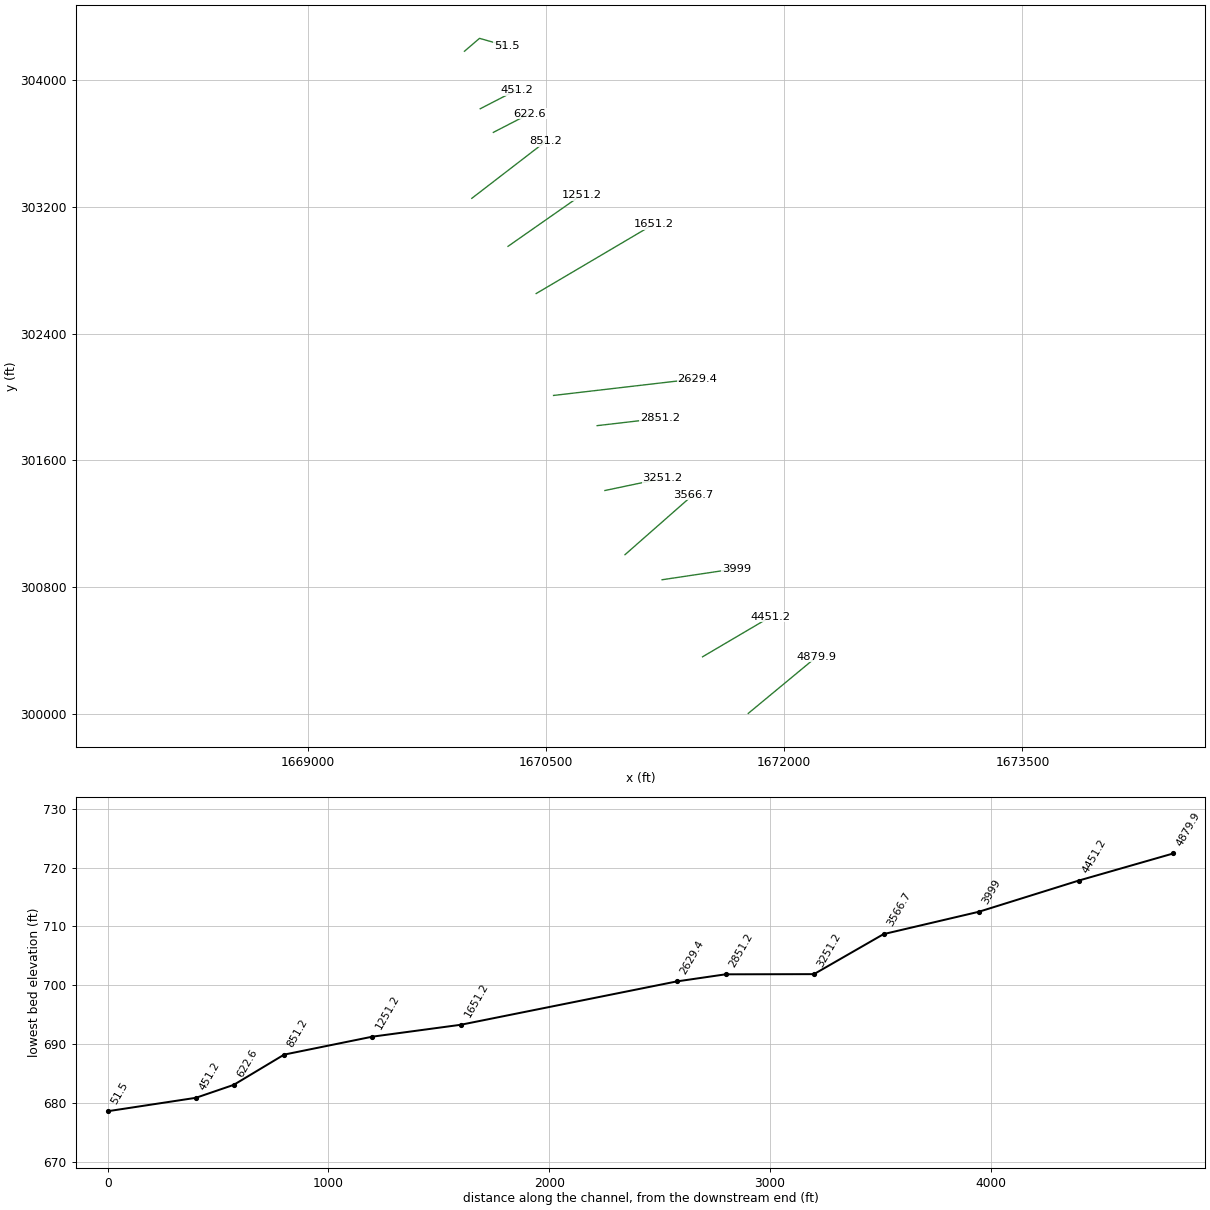
HEC-RAS study WHITMANCRK.prj: WHITMANCRK

--- WHITMANCRK.g01 (geometry) --- (continued)

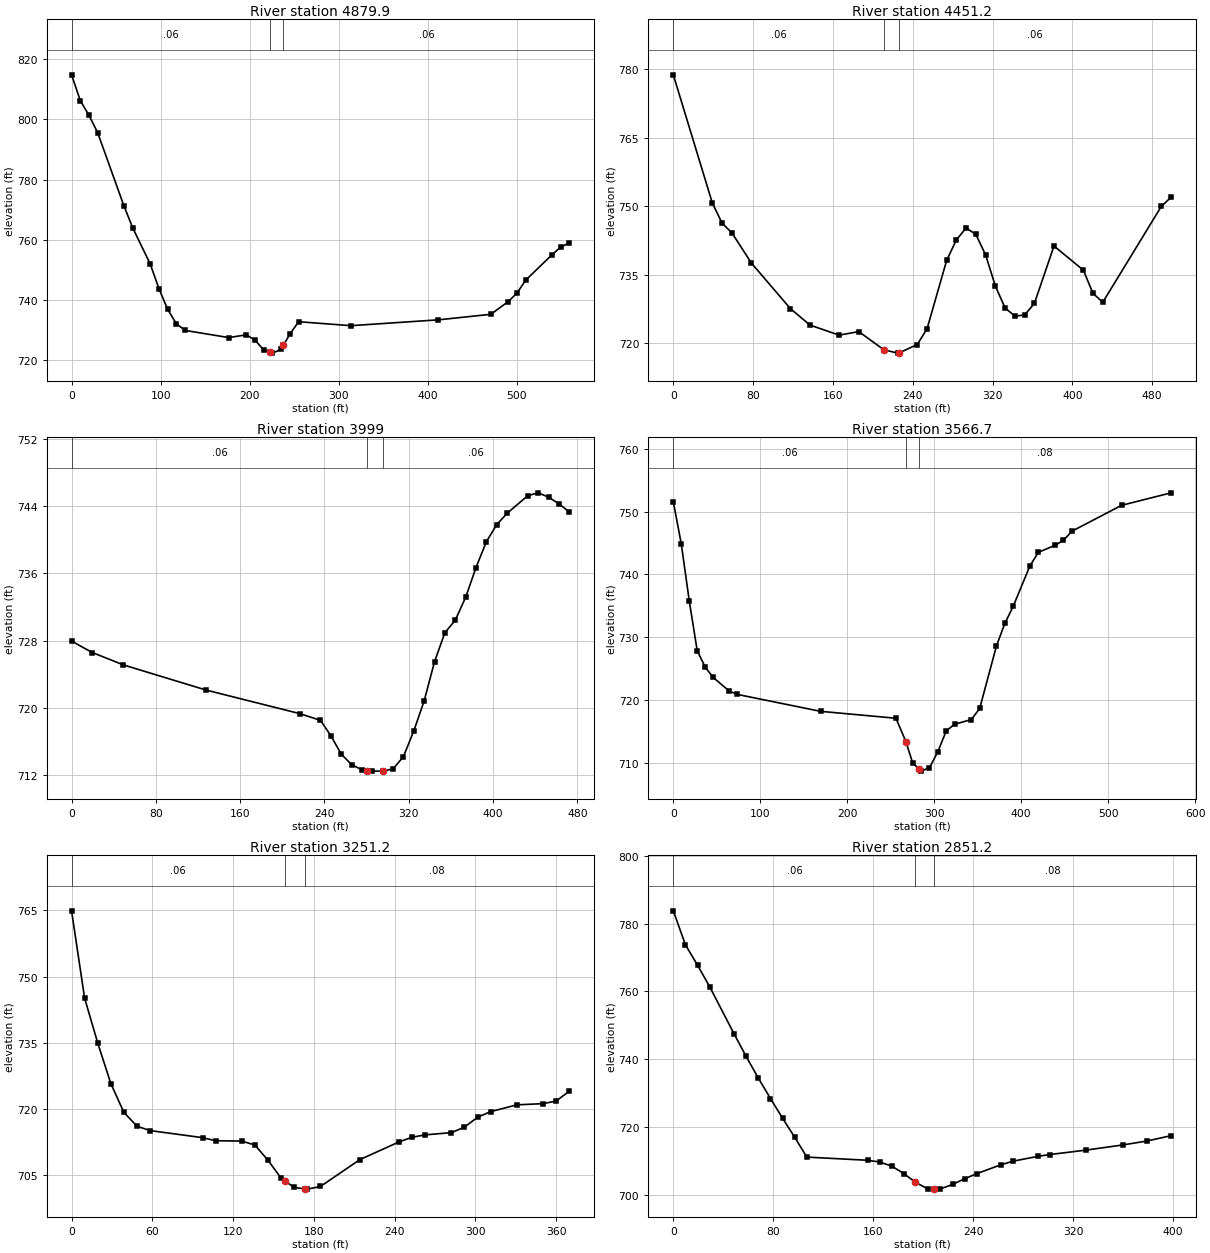
Type RM Length L Ch R = 1 ,4879.9  ,432.2,428.6,425.1
XS GIS Cut Line= 2
      1671773.83      300003.711     1672204.152      300360.565
#Sta/Elev= 30
       0  814.76     9.8  806.22    19.6  801.32    29.4  795.49    58.8  771.28
    68.6  764.02    88.3     752    98.1  743.83   107.9  736.92   117.7  732.16
   127.5  729.94   176.5  727.56   196.2  728.47     206  726.73   215.8  723.44
   222.9  722.69   225.6   722.4   235.4  723.65   237.9  724.95   245.2  728.75
     255  732.82   313.8  731.51   411.9  733.45   470.8  735.28   490.4  739.51
   500.2  742.33     510  746.62   539.4  755.02   549.2  757.58     559  758.97
#Mann= 3 , 0 , 0
       0     .06       0   222.9    .045       0   237.9     .06       0
Bank Sta=222.9,237.9
XS Rating Curve= 0 ,0
Exp/Cntr=0.3,0.1

Type RM Length L Ch R = 1 ,4451.2  ,462,452.4,442.9
XS GIS Cut Line= 2
      1671486.01      300360.814     1671915.838      300614.301
#Sta/Elev= 30
       0   778.8    39.1  750.72    48.9  746.27    58.7  744.17    78.3  737.53
   117.4  727.54     137  723.94   166.3  721.73   185.9  722.51   211.1  718.52
     225  717.79   226.1  717.82   244.6  719.68   254.4  723.15     274  738.11
   283.8  742.64   293.5  745.22   303.3  743.82   313.1  739.29   322.9  732.45
   332.7  727.65   342.5  725.91   352.2  726.14     362  728.71   381.6  741.27
     411  735.99   420.7   730.9   430.5  728.93   489.2  749.96     499  751.97
#Mann= 3 , 0 , 0
       0     .06       0   211.1    .045       0   226.1     .06       0
Bank Sta=211.1,226.1
XS Rating Curve= 0 ,0
Exp/Cntr=0.3,0.1

Type RM Length L Ch R = 1 ,3999    ,418,431.9,445.8
XS GIS Cut Line= 2
     1671231.406      300847.131     1671698.603      300917.071
#Sta/Elev= 30
       0  727.95    19.7  726.59    49.2  725.12   127.9  722.12   216.5  719.33
   236.2  718.53     246  716.72   255.9  714.52   265.7  713.27   275.6  712.64
   280.7  712.56   285.4  712.49   295.7   712.5   305.1  712.76   314.9   714.2
   324.8  717.28   334.6  720.83   344.5  725.52   354.3  728.95   364.1  730.43
     374  733.16   383.8  736.69   393.7  739.78   403.5   741.8   413.4  743.15
     433  745.25   442.9  745.58   452.7  745.06   462.6  744.27   472.4   743.3
#Mann= 3 , 0 , 0
       0     .06       0   280.7    .045       0   295.7     .06       0
Bank Sta=280.7,295.7
XS Rating Curve= 0 ,0
Exp/Cntr=0.3,0.1

Type RM Length L Ch R = 1 ,3566.7  ,327,315.4,303.7
XS GIS Cut Line= 4
     1670997.536      301005.276     1671059.488      301059.855
     1671348.636      301314.594     1671427.054      301383.679
#Sta/Elev= 30
       0  751.59     9.2  744.84    18.4  735.74    27.5  727.85    36.7  725.24
    45.9   723.6    64.2  721.45    73.4  720.91   169.3  718.21     256  717.11
   267.4   713.4   275.2  710.01   282.4  709.03   284.9  708.69   294.5  709.22
   304.1  711.74   313.8  715.09   323.4  716.15   342.7   716.9   352.3  718.67
   371.6  728.63   381.2  732.21   390.8  734.92   410.1  741.38   419.8  743.53
     439  744.65   448.6  745.43   458.3  746.88   515.4  751.01   572.4     753
#Mann= 3 , 0 , 0
       0     .06       0   267.4    .045       0   282.4     .08       0
Bank Sta=267.4,282.4
XS Rating Curve= 0 ,0
Exp/Cntr=0.3,0.1

Type RM Length L Ch R = 1 ,3251.2  ,402,400,397.9
XS GIS Cut Line= 2
     1670871.057      301410.172     1671232.908       301486.35
#Sta/Elev= 30
       0  764.88     9.7  745.12    19.5   734.9    29.2  725.77    38.9  719.24
    48.7  716.12    58.4  715.14    97.3  713.54     107  712.85   126.5  712.76
   136.2  711.87     146   708.4   155.7  704.36   158.6  703.73   165.4  702.26
   173.6  701.95   175.2  701.89   184.9  702.49   214.1  708.56   243.3  712.58
     253  713.64   262.7  714.17   282.2  714.68   291.9  715.93   301.7  718.18
   311.4  719.44   330.9  720.97   350.3  721.24     360  721.83   369.8  724.06
#Mann= 3 , 0 , 0
       0     .06       0   158.6    .045       0   173.6     .08       0
Bank Sta=158.6,173.6
XS Rating Curve= 0 ,0
Exp/Cntr=0.3,0.1

Type RM Length L Ch R = 1 ,2851.2  ,221.8,221.8,221.8
XS GIS Cut Line= 2
     1670822.103      301819.529     1671217.958      301865.712
#Sta/Elev= 30
       0  783.73     9.7  773.74    19.4  767.74    29.2  761.34    48.6  747.56
    58.3   740.9      68  734.55    77.8   728.5    87.5   722.7    97.2  717.11
   106.9  711.28   155.5  710.35   165.2  709.84     175   708.6   184.7   706.4
   193.8  703.87   204.1  701.86   208.8   701.9   213.8  701.94   223.6  703.24
   233.3  704.93     243  706.42   262.4  709.05   272.2   710.1   291.6  711.48
   301.3  712.03   330.5  713.34   359.7  714.85   379.1  716.01   398.5  717.59
#Mann= 3 , 0 , 0
       0     .06       0   193.8    .045       0   208.8     .08       0
Bank Sta=193.8,208.8
XS Rating Curve= 0 ,0
Exp/Cntr=0.3,0.1

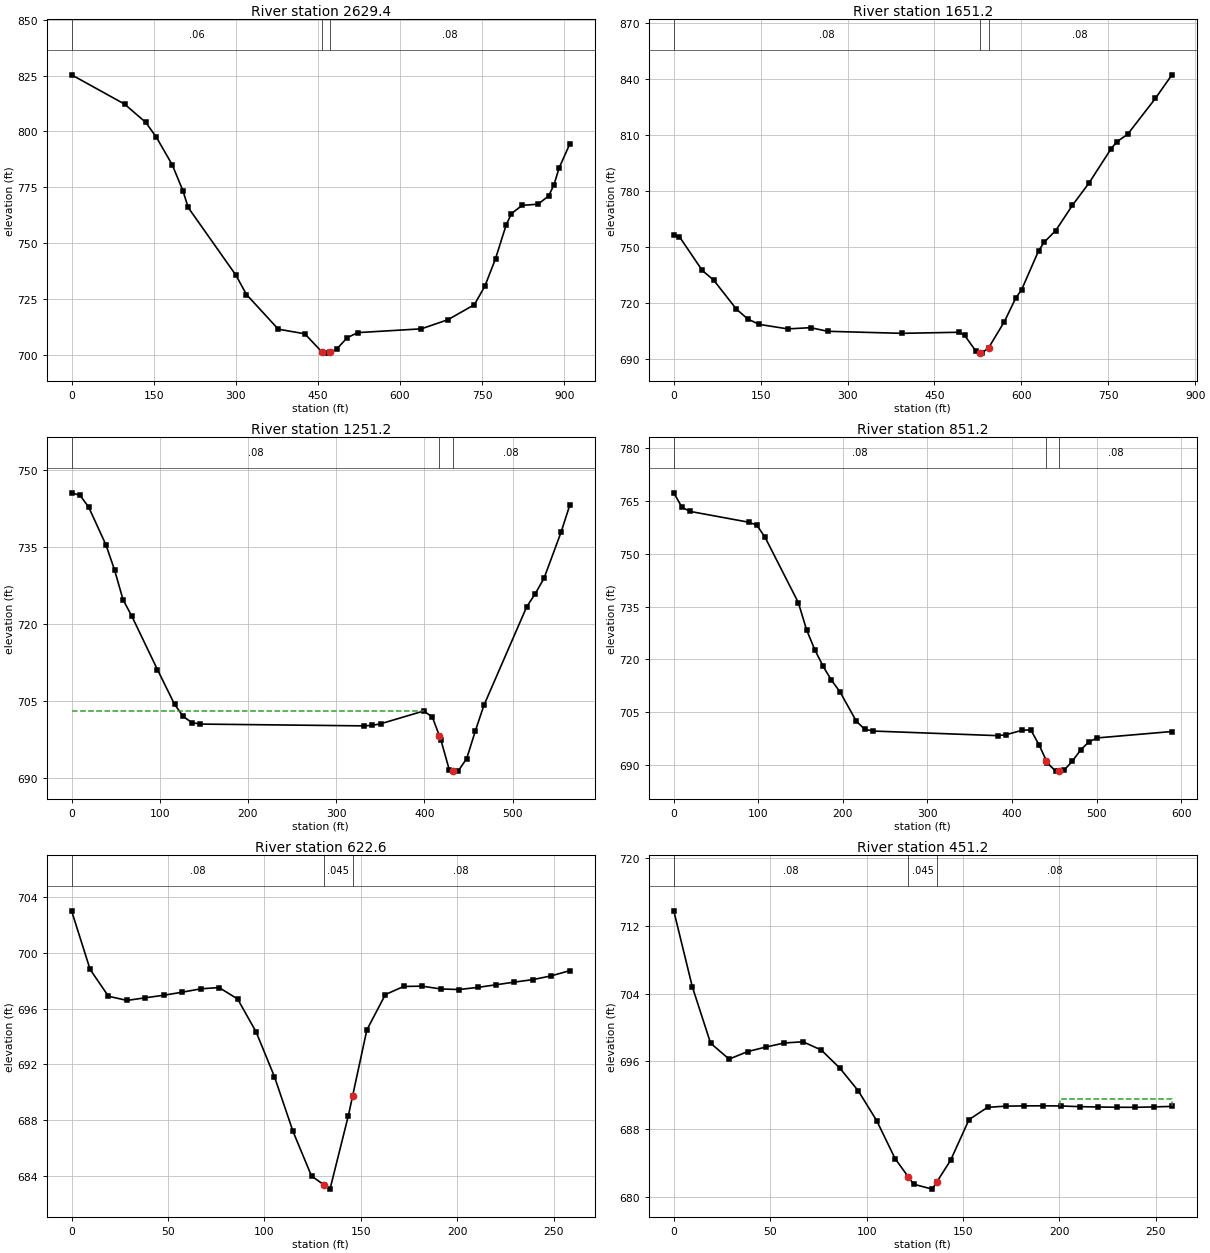
Type RM Length L Ch R = 1 ,2629.4  ,969,977.7,986.5
XS GIS Cut Line= 3
     1670547.664      302010.134     1670999.599      302062.858
     1671451.533      302115.583
#Sta/Elev= 30
       0  825.38    96.8  812.26   135.5  804.06   154.9   797.4   183.9  785.05
   203.3  773.47     213  765.92   300.1  735.62   319.5  726.91   377.6  711.38
     426  709.31   456.7  701.33   464.7  700.65   471.7  700.96     484  702.39
   503.4  707.56   522.8  709.84   638.9  711.54   687.3  715.61   735.7  722.35
   755.1  730.74   774.5  743.05   793.8  758.07   803.5  763.18   822.9  766.87
   851.9   767.4   871.3  771.04     881  775.98   890.6  783.68     910  794.34
#Mann= 3 , 0 , 0
       0     .06       0   456.7    .045       0   471.7     .08       0
Bank Sta=456.7,471.7
XS Rating Curve= 0 ,0
Exp/Cntr=0.3,0.1

Type RM Length L Ch R = 1 ,1651.2  ,397.9,400.2,402.6
XS GIS Cut Line= 3
     1670438.456      302653.299     1671014.483      302993.881
     1671178.669      303090.957
#Sta/Elev= 30
       0  756.55     9.8  755.57    49.2  737.52    68.9  732.36   108.2  716.81
   127.9  711.51   147.6  708.66   196.8  706.25   236.2  706.91   265.7  704.97
   393.6  703.88     492  704.45   501.9  702.85   521.6  694.36   528.5  693.61
   531.4  693.29   543.5  696.15   570.8   710.2   590.4  722.84   600.3  727.12
   629.8   748.1   639.7  752.74   659.3  758.87   688.2  772.42   716.9  784.35
     755   802.7   764.6  806.31   783.6  810.45   831.3  829.55   859.9  842.19
#Mann= 3 , 0 , 0
       0     .08       0   528.5    .045       0   543.5     .08       0
Bank Sta=528.5,543.5
XS Rating Curve= 0 ,0
Exp/Cntr=0.3,0.1

Type RM Length L Ch R = 1 ,1251.2  ,398.9,400,401
XS GIS Cut Line= 2
     1670261.067      302951.299     1670723.611      303275.376
#Sta/Elev= 30
       0  745.57     9.7  745.07    19.5  742.74      39   735.4    48.7  730.54
    58.4  724.69    68.2  721.54    97.4  711.06   116.8  704.29   126.6  701.93
   136.3  700.75   146.1  700.45   331.1   700.1   340.8  700.19   350.6  700.52
   399.2     703     409  701.83   417.1  698.11   418.7  697.37   428.4  691.41
   432.1  691.36   438.2  691.27   447.9   693.7   457.7  699.07   467.4  704.08
   516.1  723.37   525.8  725.92   535.6  728.89     555  737.91   564.8  743.15
#Mann= 3 , 0 , 0
       0     .08       0   417.1    .045       0   432.1     .08       0
#XS Ineff= 2 , 0
             400  703.08
Permanent Ineff=
       F       F
Bank Sta=417.1,432.1
XS Rating Curve= 0 ,0
Exp/Cntr=0.3,0.1

Type RM Length L Ch R = 1 ,851.2   ,232.6,228.5,224.4
XS GIS Cut Line= 2
     1670033.058      303254.314      1670499.46      303614.112
#Sta/Elev= 30
       0  767.37     9.8  763.22    19.6  762.07    88.4  759.02    98.2  758.19
     108   754.7   147.3  736.14   157.1  728.37   166.9  722.66   176.7  717.99
   186.5  714.06   196.4  710.81     216  702.37   225.8  700.13   235.6  699.62
   382.9  698.31   392.7  698.56   412.3  699.87   422.2  699.92     432  695.63
   440.4  691.24   441.8  690.51   451.6  688.22   455.4  688.31   461.4  688.45
   471.2  691.05   481.1  694.24   490.9  696.56   500.7  697.66     589  699.49
#Mann= 3 , 0 , 0
       0     .08       0   440.4    .045       0   455.4     .08       0
Bank Sta=440.4,455.4
XS Rating Curve= 0 ,0
Exp/Cntr=0.3,0.1

Type RM Length L Ch R = 1 ,622.6   ,171.3,171.4,171.4
XS GIS Cut Line= 2
     1670168.554      303670.416     1670398.115      303788.909
#Sta/Elev= 30
       0  702.99     9.6   698.8    19.1  696.88    28.7  696.58    38.3  696.77
    47.8  696.95    57.4  697.17      67  697.41    76.5   697.5    86.1  696.68
    95.7  694.32   105.2  691.12   114.8  687.21   124.4  684.02   130.7   683.4
     134  683.08   143.5  688.33   145.7  689.74   153.1  694.47   162.7     697
   172.2  697.58   181.8   697.6   191.4   697.4   200.9  697.36   210.5  697.51
   220.1   697.7   229.6  697.89   239.2  698.07   248.8  698.34   258.3  698.71
#Mann= 3 , 0 , 0
       0     .08       0   130.7    .045       0   145.7     .08       0
Bank Sta=130.7,145.7
XS Rating Curve= 0 ,0
Exp/Cntr=0.3,0.1

Type RM Length L Ch R = 1 ,451.2   ,416.6,399.6,382.5
XS GIS Cut Line= 2
     1670085.853       303819.46     1670315.413      303937.953
#Sta/Elev= 30
       0  713.78     9.6  704.82    19.1  698.13    28.7  696.25    38.3  697.14
    47.8  697.68    57.4  698.16      67   698.3    76.5  697.32    86.1  695.19
    95.7  692.49   105.2  688.98   114.8  684.47   121.5  682.37   124.4  681.46
     134  680.88   136.5  681.77   143.5  684.27   153.1   689.1   162.7  690.55
   172.2  690.69   181.8  690.72   191.4  690.73   200.9  690.71   210.5  690.63
   220.1  690.59   229.6  690.56   239.2  690.55   248.8   690.6   258.3  690.66
#Mann= 3 , 0 , 0
       0     .08       0   121.5    .045       0   136.5     .08       0
#XS Ineff= 2 , 0
                          200.46          691.54
Permanent Ineff=
       F       F
Bank Sta=121.5,136.5
XS Rating Curve= 0 ,0
Exp/Cntr=0.3,0.1

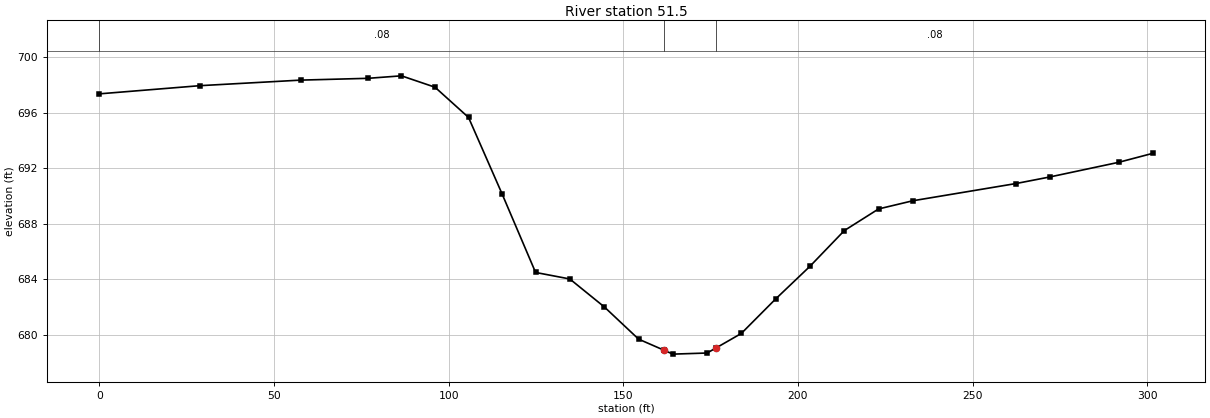
Type RM Length L Ch R = 1 ,51.5    ,51.2,51.5,51.8
XS GIS Cut Line= 3
     1669986.649      304182.356     1670081.357      304263.805
     1670251.266      304215.256
#Sta/Elev= 26
       0  697.37    28.8  697.96    57.6  698.36    76.9  698.49    86.5  698.67
    96.1  697.85   105.7  695.67   115.3  690.16   124.9  684.49   134.7  684.02
   144.6     682   154.4  679.68   161.6  678.89   164.2   678.6     174  678.68
   176.6  679.05   183.8  680.09   193.6  682.57   203.4  684.92   213.3  687.51
   223.1  689.07   232.9  689.66   262.4   690.9   272.2  691.38   291.8  692.43
   301.6  693.08
#Mann= 3 , 0 , 0
       0     .08       0   161.6    .045       0   176.6     .08       0
Bank Sta=161.6,176.6
XS Rating Curve= 0 ,0
Exp/Cntr=0.3,0.1

Chan Stop Cuts=-1
Use User Specified Reach Order=0
Composite Channel Slope=5